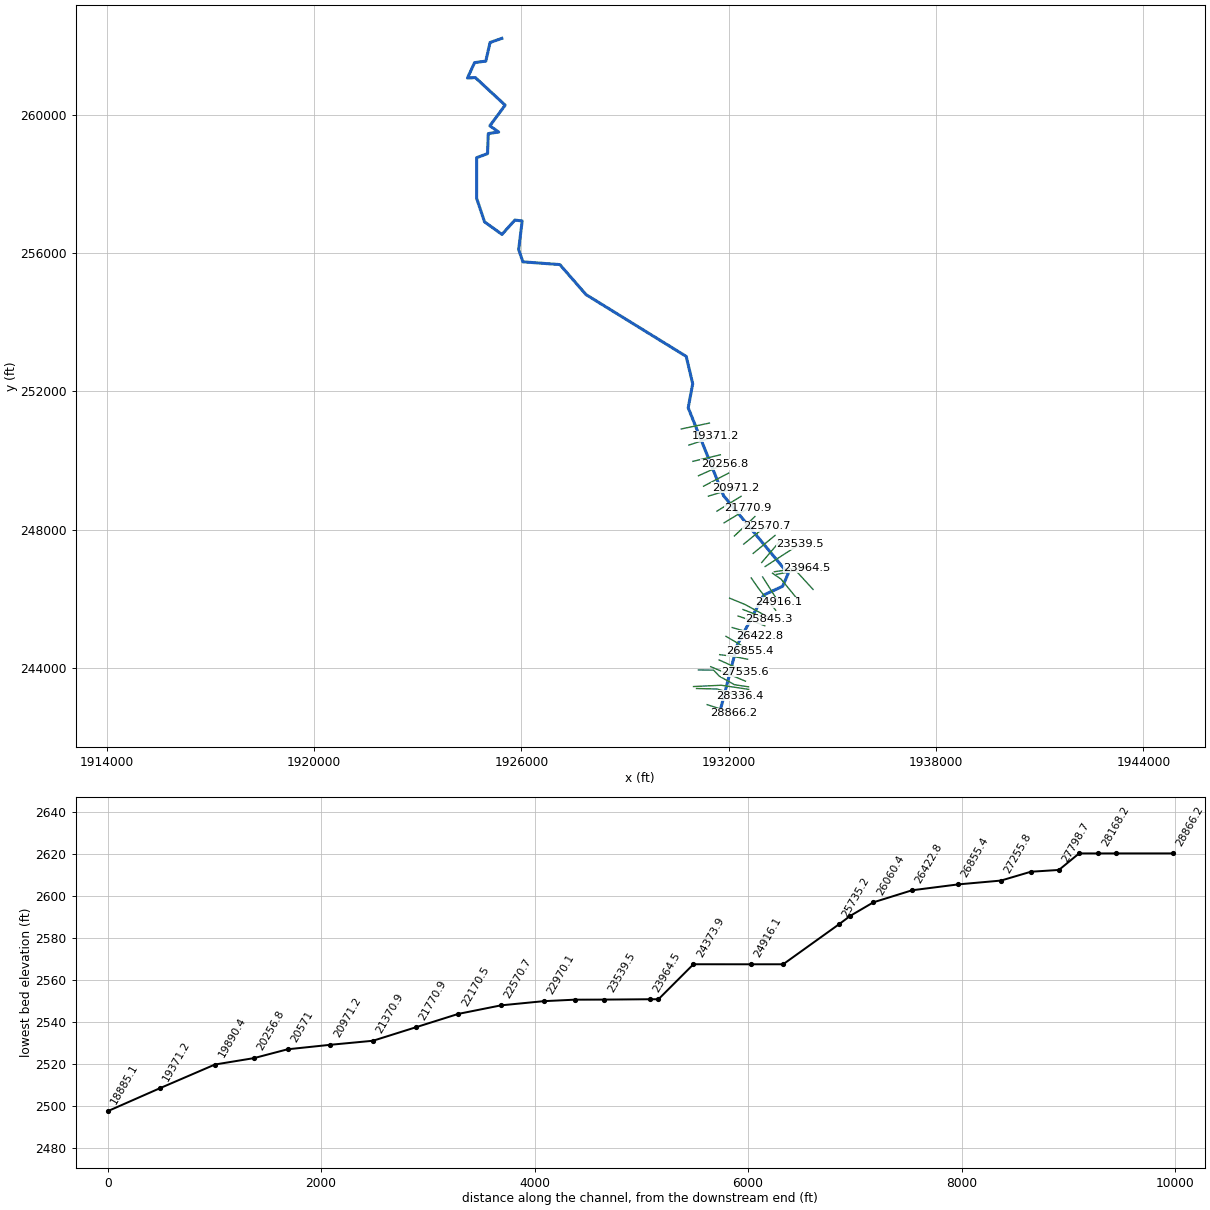
--- BvrCrk.prj (project) ---

Proj Title=BvrCrk
Current Plan=p01
Default Exp/Contr=0,0
English Units
Geom File=g01
Flow File=f01
Plan File=p01
BEGIN DESCRIPTION:
END DESCRIPTION:
DSS Export Rating Curves= 0
DSS Export Rating Curve Sorted= 0
DSS Export Volume Flow Curves= 0
DXF OffsetX= 0
DXF OffsetY= 0
DXF ScaleX= 0
DXF ScaleY= 0

--- BvrCrk.p01 (plan) ---

Plan Title=Floodplain
Program Version=4.00
Geom File=g01
Flow File=f01
K Sum by GR=0
Std Step Tol=0.01
Critical Tol=0.01
Num of Std Step Trials=20
Max Error Tol=0.3
Flow Tol Ratio=0.001
Split Flow NTrial=30
Split Flow Tol=0.02
Split Flow Ratio=0.02
Log Output Level=0
Friction Slope Method=1
Unsteady Friction Slope Method=2
Unsteady Bridges Friction Slope Method=1
Global Log Level=0
CheckData=False
Run HTab=0
Run UNet=0
Run PostProcess=0
UNET Theta=0
UNET Theta Warmup=0
UNET ZTol=0
UNET ZSATol=0
UNET MxIter=0
UNET MaxInSteps=0
UNET DtIC=0
UNET DtMin=0
UNET MaxCRTS=0
UNET WFStab=0
UNET SFStab=0
UNET WFX=0
UNET SFX=0
UNET DSS MLevel=0
UNET DZMax Abort=0
UNET Convert EG Bridges=0
UNET Use Existing IB Tables=0
UNET Froude Limit=0
UNET Froude Power=0
Write IC File=0
Echo Input=False
Echo Output=False
Write Detailed=0

--- BvrCrk.f01 (steady flow) ---

Flow Title=NFF Regression Equation
Program Version=4.10
Number of Profiles= 1
Profile Names=P100yr
River Rch & RM=BvrCrk,Main            ,28866.2
375.3533
River Rch & RM=BvrCrk,Main            ,28336.4
596.3137
River Rch & RM=BvrCrk,Main            ,25735.2
661.3199
River Rch & RM=BvrCrk,Main            ,25214.9
728.5631
River Rch & RM=BvrCrk,Main            ,24046.2
736.1474
River Rch & RM=BvrCrk,Main            ,23539.5
1421.618
River Rch & RM=BvrCrk,Main            ,19890.4
1491.869
River Rch & RM=BvrCrk,Main            ,11790.6
1647.025
River Rch & RM=BvrCrk,Main            ,11505.9
2212.906
River Rch & RM=BvrCrk,Main            ,10840.4
2215.781
River Rch & RM=BvrCrk,Main            ,10157.1
2461.188
River Rch & RM=BvrCrk,Main            ,393.8
2656.738
Boundary for River Rch & Prof#=BvrCrk,Main            , 1
Up Type= 0
Dn Type= 1
Dn Known WS=2290.5
DSS Import GetInterval= 0
DSS Import GetPeak= 0
DSS Import FillOption= 0

--- BvrCrk.g01 (geometry) ---

Geom Title=USGS 3m DEM
Program Version=4.10

River Reach=BvrCrk          ,Main
Reach XY= 30
     1931763.899      242804.904     1932241.876        244653.6
      1933012.01      246106.669     1933560.887      246360.631
     1933719.741      246726.517     1931850.375      248980.937
     1930828.061      251522.885     1930958.264      252217.508
     1930770.522      253007.767     1927870.662      254795.498
     1927114.012      255663.227      1926043.77      255742.824
     1925922.413      256095.638     1926023.126      256925.736
     1925810.886      256949.173     1925439.047      256536.229
     1924933.282      256899.694     1924704.116       257584.59
      1924706.72      258755.163     1925021.824       258872.35
     1925042.083      259451.262     1925343.439      259496.048
      1925088.23      259675.736     1925530.556      260273.694
     1924667.903      261072.047     1924439.811      261058.123
      1924646.78      261503.647     1924970.986      261547.154
     1925094.057       262085.38     1925436.325      262206.017

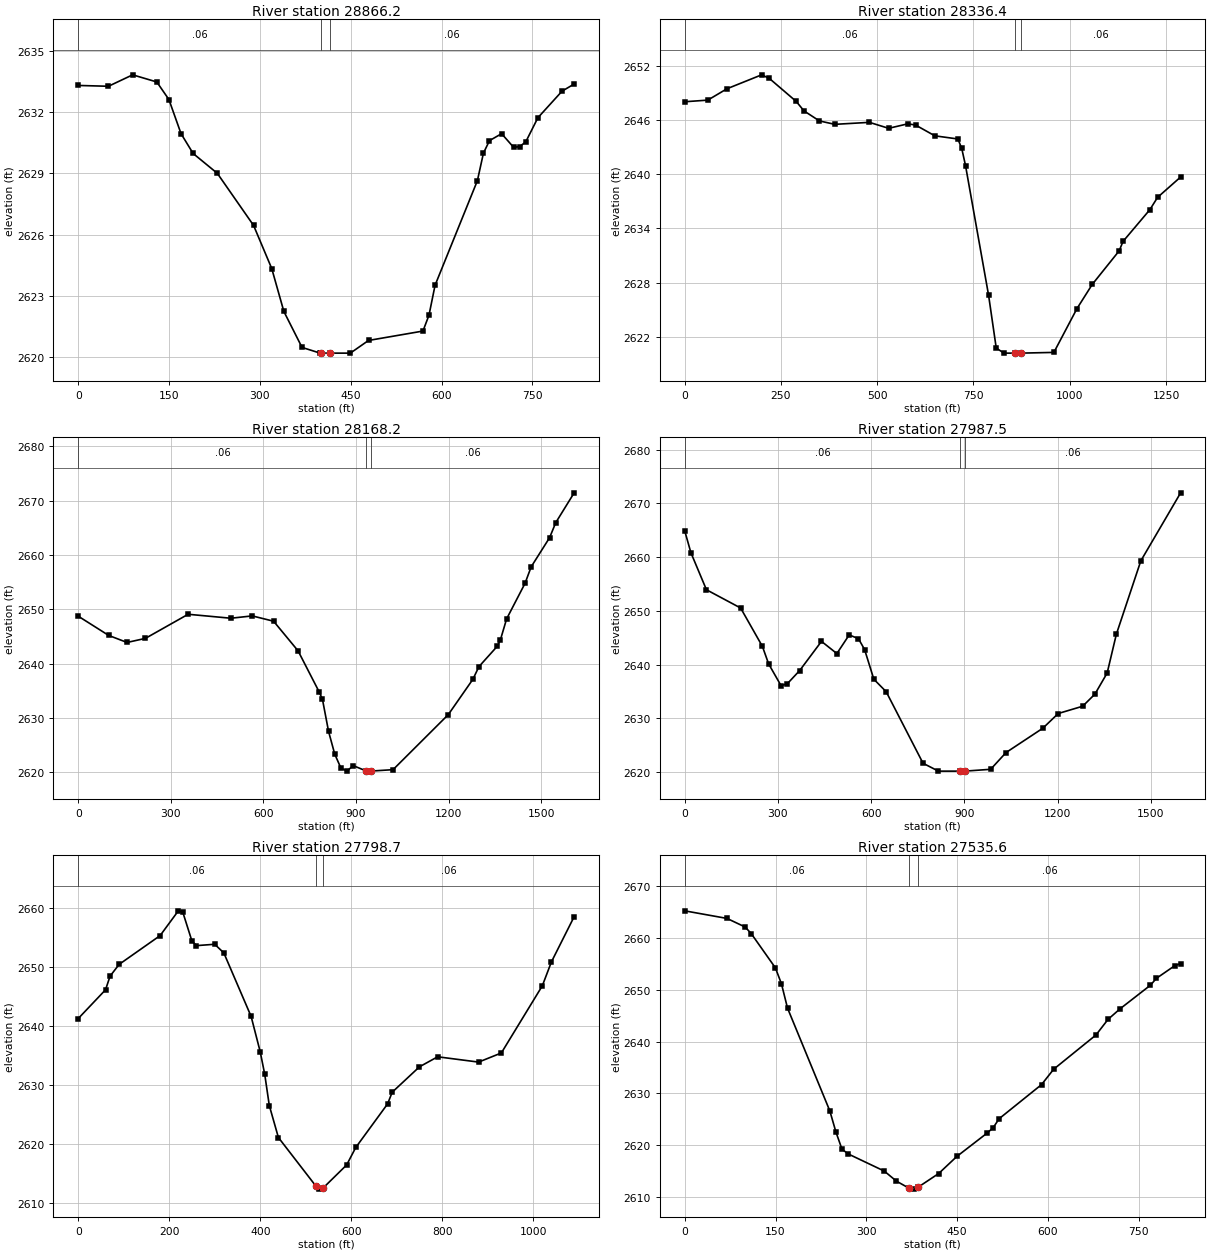
Type RM Length L Ch R = 1 ,28866.2 ,529.5,529.9,530.3
XS GIS Cut Line= 3
     1931377.347      242937.166     1931766.977      242811.154
     1932156.607      242685.143
#Sta/Elev= 30
       0  2633.3    49.9 2633.26    89.9 2633.82   129.8 2633.47   149.8 2632.61
   169.8 2630.94   189.8 2629.97   229.7    2629   289.6 2626.45   319.6 2624.34
   339.6 2622.24   369.6 2620.48   399.5  2620.2     401  2620.2     416  2620.2
   449.4  2620.2   479.4 2620.82   569.3 2621.28   579.3 2622.06   589.3 2623.52
   659.2 2628.64   669.2 2629.99   679.2  2630.6   699.2 2630.94   719.1 2630.27
   729.1 2630.31   739.1 2630.54   759.1 2631.72     799 2633.02     819 2633.37
#Mann= 3 , 0 , 0
       0     .06       0     401    .045       0     416     .06       0
Bank Sta=401,416
XS Rating Curve= 0 ,0
Exp/Cntr=0.3,0.1

Type RM Length L Ch R = 1 ,28336.4 ,165.3,168.1,170.9
XS GIS Cut Line= 3
     1931068.216      243404.225     1931667.705      243389.343
     1932327.534      243193.593
#Sta/Elev= 30
       0 2648.02      60  2648.2   109.9 2649.46   199.9    2651   219.9  2650.6
   289.8 2648.05   309.8 2647.01   349.8  2645.9   389.8 2645.52   479.7 2645.74
   529.7 2645.08   579.7 2645.58   599.7 2645.44   649.6 2644.25   709.4  2643.9
   719.4 2642.87   729.3 2640.96   789.2 2626.61   809.1 2620.76   829.1  2620.2
   858.2  2620.2   873.2  2620.2   958.8 2620.28  1018.6 2625.12  1058.5 2627.81
  1128.3 2631.52  1138.3 2632.56  1208.1 2636.08  1228.1 2637.44  1287.9 2639.69
#Mann= 3 , 0 , 0
       0     .06       0   858.2    .045       0   873.2     .06       0
Bank Sta=858.2,873.2
XS Rating Curve= 0 ,0
Exp/Cntr=0.3,0.1

Type RM Length L Ch R = 1 ,28168.2 ,191.2,180.7,170.2
XS GIS Cut Line= 3
     1930981.381      243461.383     1931781.684      243498.566
     1932578.446      243379.937
#Sta/Elev= 30
       0 2648.72    98.9 2645.17   158.3 2643.88   217.6 2644.63   356.1 2649.07
   494.6 2648.34   563.8 2648.77     633 2647.79   712.2 2642.34   781.4 2634.69
   791.3  2633.4   811.1 2627.49     831 2623.33   850.9 2620.77   870.8 2620.19
   890.7 2621.21   933.8  2620.2   948.8  2620.2    1020 2620.46    1199  2630.6
  1278.5 2637.09  1298.4 2639.44  1358.1 2643.21    1368  2644.4  1387.9 2648.22
  1447.6 2654.77  1467.5 2657.81  1527.2 2663.18    1547 2665.93  1606.7 2671.43
#Mann= 3 , 0 , 0
       0     .06       0   933.8    .045       0   948.8     .06       0
Bank Sta=933.8,948.8
XS Rating Curve= 0 ,0
Exp/Cntr=0.3,0.1

Type RM Length L Ch R = 1 ,27987.5 ,183.9,188.9,193.8
XS GIS Cut Line= 5
     1931123.028      243941.211     1931563.246      243935.278
     1931726.796      243762.382     1932165.901      243514.501
     1932574.905      243452.531
#Sta/Elev= 30
       0 2664.91      20 2660.82      70 2653.93   180.1 2650.53   250.2 2643.39
   270.2 2640.14   310.2 2636.09   330.2 2636.44   370.2 2638.91   440.3 2644.33
   489.8 2642.06   529.5 2645.53   559.3 2644.83   579.1  2642.8   608.8 2637.29
   648.5 2634.97   767.2 2621.66   816.7  2620.2   886.9  2620.2   901.9  2620.2
   984.8 2620.54  1034.2 2623.65  1152.8 2628.18  1202.2 2630.91    1281 2632.27
  1320.4 2634.52  1359.8 2638.45  1389.3 2645.64  1468.1  2659.3  1596.2 2671.95
#Mann= 3 , 0 , 0
       0     .06       0   886.9    .045       0   901.9     .06       0
Bank Sta=886.9,901.9
XS Rating Curve= 0 ,0
Exp/Cntr=0.3,0.1

Type RM Length L Ch R = 1 ,27798.7 ,263.6,263,262.4
XS GIS Cut Line= 2
     1931478.915      244035.052     1932484.681      243616.695
#Sta/Elev= 30
       0 2641.24      60 2646.12      70 2648.44    89.9 2650.43   179.9 2655.31
   219.9 2659.51   229.8 2659.26   249.8 2654.38   259.8 2653.61   299.8 2653.84
   319.8 2652.38   379.8  2641.6   399.8 2635.59   409.7 2631.78   419.7  2626.5
   439.7 2621.07     522 2612.84   529.7 2612.32     537 2612.44   589.6 2616.42
   609.6 2619.38   679.6 2626.78   689.6 2628.75   749.5 2633.06   789.5 2634.76
   879.4 2633.86   929.4 2635.41  1019.4  2646.8  1039.3 2650.84  1089.3 2658.52
#Mann= 3 , 0 , 0
       0     .06       0     522    .045       0     537     .06       0
Bank Sta=522,537
XS Rating Curve= 0 ,0
Exp/Cntr=0.3,0.1

Type RM Length L Ch R = 1 ,27535.6 ,273.1,279.8,284.8
XS GIS Cut Line= 3
     1931722.275      244229.831     1932095.903      244062.225
     1932469.531      243894.618
#Sta/Elev= 30
       0 2665.26    69.9 2663.79    99.9 2662.13   109.9 2660.86   149.8 2654.24
   159.8 2651.16   169.8 2646.47   239.7 2626.59   249.7 2622.53   259.7 2619.21
   269.7 2618.29   329.6 2614.96   349.6 2613.02   371.1 2611.61   379.5 2611.47
   386.1 2611.89   419.5 2614.49   449.4 2617.78   499.4  2622.3   509.4 2623.34
   519.4 2625.09   589.3 2631.67   609.3 2634.64   679.2 2641.26   699.2 2644.29
   719.1 2646.33   769.1 2650.88     779 2652.21     809 2654.63     819 2655.07
#Mann= 3 , 0 , 0
       0     .06       0   371.1    .045       0   386.1     .06       0
Bank Sta=371.1,386.1
XS Rating Curve= 0 ,0
Exp/Cntr=0.3,0.1

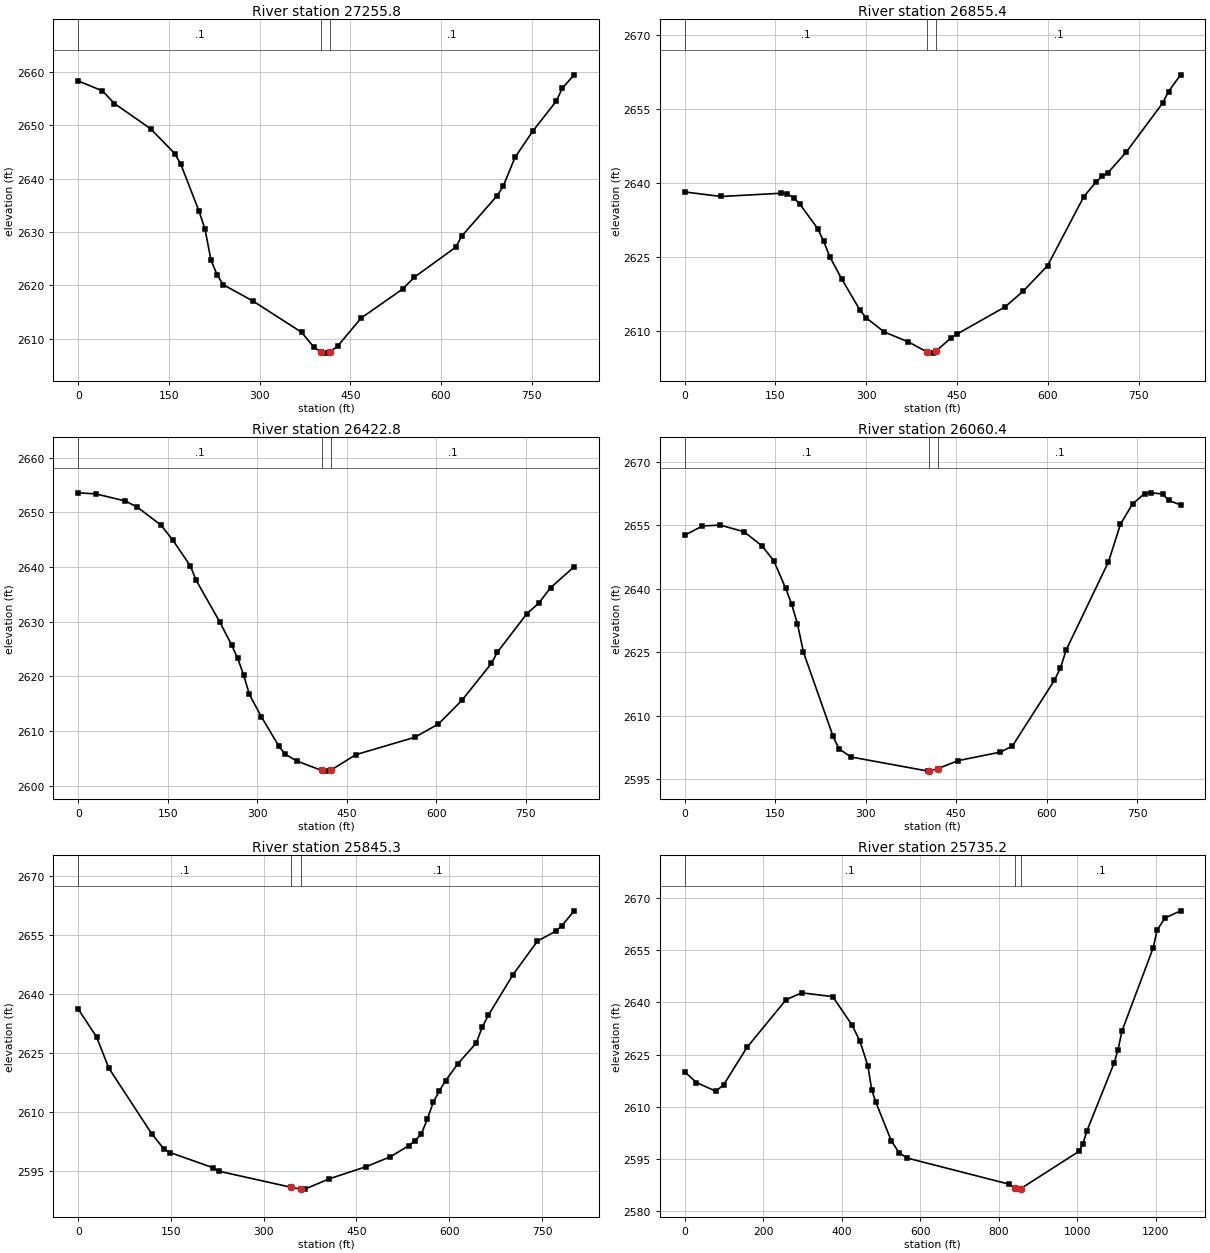
Type RM Length L Ch R = 1 ,27255.8 ,409.5,400.4,392.2
XS GIS Cut Line= 3
     1931738.231      244383.682     1932144.154      244331.419
      1932546.76      244249.848
#Sta/Elev= 30
       0  2658.3    39.9 2656.44    59.9 2654.06   119.8 2649.32   159.7 2644.67
   169.7 2642.66   199.6 2633.93   209.6 2630.54   219.6 2624.68   229.6 2621.96
   239.6  2620.1   289.5 2616.99   369.3 2611.17   389.3 2608.42   401.4 2607.47
   409.3 2607.26   416.4  2607.5   428.8 2608.55     468 2613.85   536.4 2619.27
     556 2621.51   624.4 2627.13   634.2  2629.2   692.9  2636.8   702.7 2638.53
   722.2 2643.94   751.6 2648.87   790.7 2654.53   800.5 2656.93   820.1 2659.44
#Mann= 3 , 0 , 0
       0      .1       0   401.4    .045       0   416.4      .1       0
Bank Sta=401.4,416.4
XS Rating Curve= 0 ,0
Exp/Cntr=0.3,0.1

Type RM Length L Ch R = 1 ,26855.4 ,426.6,432.5,439.2
XS GIS Cut Line= 3
     1931921.204      244913.094     1932274.679      244706.446
     1932621.145      244487.605
#Sta/Elev= 30
       0  2638.1    59.9 2637.18   159.8 2637.84   169.8 2637.69   179.8 2636.92
   189.7 2635.71   219.7 2630.68   229.7 2628.08   239.7 2624.96   259.6 2620.42
   289.6 2614.15   299.6 2612.61   329.6 2609.73   369.5 2607.71   400.3 2605.68
   409.4 2605.44   415.3 2605.88   439.4 2608.46   449.4 2609.27   529.4 2614.82
   559.4 2618.02   599.4 2623.16   659.3 2637.15   679.3 2640.09   689.3 2641.23
   699.3    2642   729.3 2646.16   789.3 2656.07   799.2 2658.45   819.2 2661.83
#Mann= 3 , 0 , 0
       0      .1       0   400.3    .045       0   415.3      .1       0
Bank Sta=400.3,415.3
XS Rating Curve= 0 ,0
Exp/Cntr=0.3,0.1

Type RM Length L Ch R = 1 ,26422.8 ,363.4,362.3,360.5
XS GIS Cut Line= 2
     1932102.795      245167.671     1932899.379       244931.46
#Sta/Elev= 30
       0 2653.56    29.7 2653.36    79.1 2652.06    98.9 2650.95   138.5 2647.66
   158.3 2644.95   187.9 2640.17   197.8 2637.52   237.4 2629.89   257.2 2625.68
   267.1 2623.29     277 2620.29   286.8 2616.68   306.6 2612.63   336.3 2607.19
   346.2 2605.79     366  2604.5   407.8 2602.77   415.4 2602.64   422.8 2602.78
   464.9 2605.64   563.8 2608.83   603.4 2611.25   642.9  2615.6   692.4 2622.37
   702.3 2624.41   751.7 2631.45   771.5 2633.36   791.3 2636.19   830.9 2640.03
#Mann= 3 , 0 , 0
       0      .1       0   407.8    .045       0   422.8      .1       0
Bank Sta=407.8,422.8
XS Rating Curve= 0 ,0
Exp/Cntr=0.3,0.1

Type RM Length L Ch R = 1 ,26060.4 ,216,215,214.9
XS GIS Cut Line= 3
     1932271.322      245500.572     1932662.268      245366.059
     1933043.491      245218.444
#Sta/Elev= 30
       0 2652.64    29.5 2654.84    59.1 2655.04    98.4 2653.47     128 2650.15
   147.7 2646.63   167.3 2640.15   177.2 2636.42     187 2631.68   196.9    2625
   246.1  2605.1   255.9 2602.15   275.6 2600.25   403.6  2596.9   404.8 2596.93
   419.8 2597.49   453.3 2599.38   523.1 2601.39   543.1 2602.78   612.9 2618.36
   622.8 2621.21   632.8 2625.64   702.6 2646.36   722.5 2655.28   742.5 2660.03
   762.4  2662.5   772.4 2662.67   792.3 2662.41   802.3 2660.88   822.2 2659.81
#Mann= 3 , 0 , 0
       0      .1       0   404.8    .045       0   419.8      .1       0
Bank Sta=404.8,419.8
XS Rating Curve= 0 ,0
Exp/Cntr=0.3,0.1

Type RM Length L Ch R = 1 ,25845.3 ,113.1,110.1,107.1
XS GIS Cut Line= 2
     1932413.858      245688.276     1933162.814      245401.441
#Sta/Elev= 30
       0 2636.18    29.7 2629.08    49.5 2621.19   118.8 2604.56   138.6 2600.67
   148.5 2599.78   217.8 2595.94   227.7 2595.04   344.7 2590.95   359.7 2590.51
   366.4  2590.5     406 2593.12   465.4 2596.18     505 2598.72   534.7 2601.54
   544.6 2602.76   554.5 2604.36   564.4 2608.19   574.3 2612.58   584.2 2615.47
   594.1    2618   613.9 2622.28   643.6 2627.55   653.5 2631.65   663.4 2634.63
     703 2644.86   742.6 2653.39   772.3 2655.94   782.2 2657.31     802 2661.08
#Mann= 3 , 0 , 0
       0      .1       0   344.7    .045       0   359.7      .1       0
Bank Sta=344.7,359.7
XS Rating Curve= 0 ,0
Exp/Cntr=0.3,0.1

Type RM Length L Ch R = 1 ,25735.2 ,529.5,520.2,510.8
XS GIS Cut Line= 3
     1932026.101      246017.604     1932475.828      245831.693
     1933158.947      245460.646
#Sta/Elev= 30
       0 2620.06    29.8 2616.96    79.4 2614.46    99.3 2616.31   158.9 2627.06
   258.2 2640.71   297.9 2642.72   377.4 2641.63     427 2633.38   446.9 2628.76
   466.8 2621.82   476.7 2614.89   486.6 2611.47   526.5 2600.24   546.4 2596.81
   566.4 2595.29   825.5  2587.8   841.7 2586.59   845.4 2586.34   856.7 2586.49
  1004.9 2597.19  1014.9 2599.32  1024.8 2602.96  1094.6 2622.59  1104.6 2626.44
  1114.5 2631.75  1194.3  2655.7  1204.2  2660.8  1224.2 2664.21    1264 2666.27
#Mann= 3 , 0 , 0
       0      .1       0   841.7    .045       0   856.7      .1       0
Bank Sta=841.7,856.7
XS Rating Curve= 0 ,0
Exp/Cntr=0.3,0.1

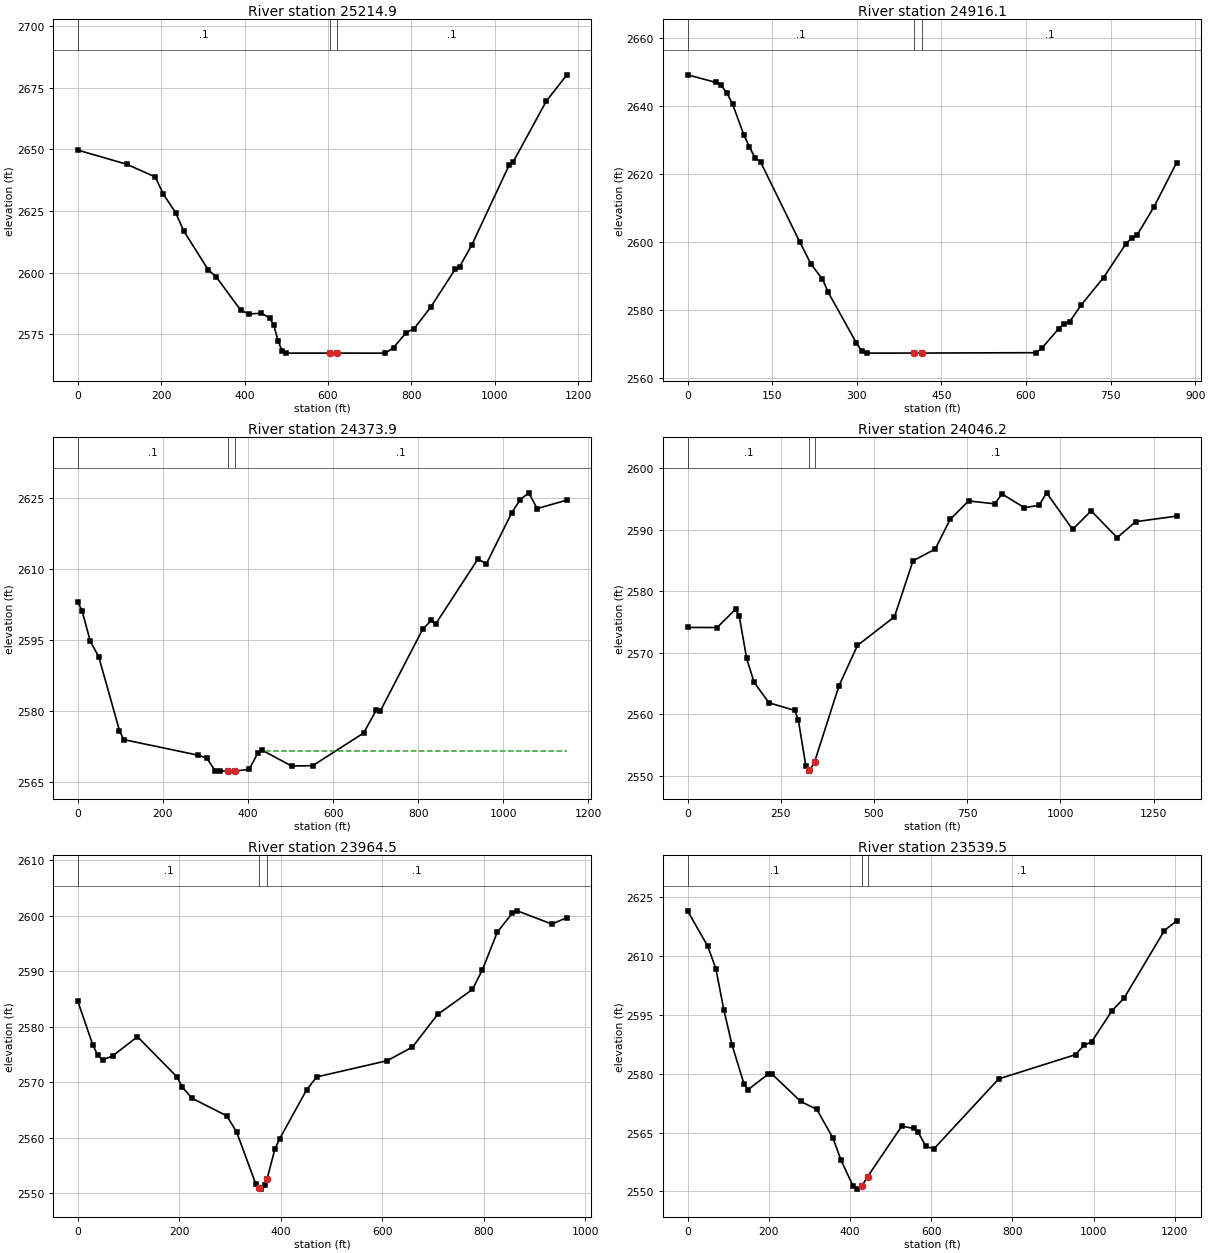
Type RM Length L Ch R = 1 ,25214.9 ,298.9,298.6,297.4
XS GIS Cut Line= 3
     1932651.116      246601.896     1932863.586      246297.356
     1933359.349      245667.029
#Sta/Elev= 30
       0 2649.66   117.3 2643.93   185.7 2638.79   205.2 2631.74   234.5 2624.35
   254.1 2616.86   312.7 2601.19   332.2 2598.24   391.1 2584.69   410.9 2583.28
   440.6 2583.55   460.4 2581.59   470.3 2578.64   480.2 2572.42   490.1 2568.35
     500  2567.4   605.6  2567.4   620.6  2567.4   737.6 2567.39   757.4 2569.61
   787.2 2575.61     807 2577.36   846.6 2586.02     906 2601.56   915.8  2602.4
   945.6 2611.36  1034.7 2643.55  1044.6  2644.9  1123.8 2669.46  1173.3 2680.17
#Mann= 3 , 0 , 0
       0      .1       0   605.6    .045       0   620.6      .1       0
Bank Sta=605.6,620.6
XS Rating Curve= 0 ,0
Exp/Cntr=0.3,0.1

Type RM Length L Ch R = 1 ,24916.1 ,539.5,541.9,541.7
XS GIS Cut Line= 2
     1932981.841      246630.241     1933446.753      245898.375
#Sta/Elev= 30
       0  2649.1    49.8 2646.89    59.8    2646    69.8 2643.74    79.7 2640.56
    99.7 2631.55   109.6 2627.94   119.6 2624.75   129.6 2623.47   199.3  2599.9
   219.2 2593.44   239.2 2589.14   249.2  2585.3     299 2570.48     309 2567.94
   318.9 2567.38   401.1  2567.4   416.1  2567.4   617.9 2567.51   627.9 2568.76
   657.8 2574.53   667.7 2576.04   677.7 2576.65   697.6 2581.46   737.5 2589.56
   777.4 2599.53   787.3 2601.09   797.3 2602.11   827.2 2610.38     867 2623.28
#Mann= 3 , 0 , 0
       0      .1       0   401.1    .045       0   416.1      .1       0
Bank Sta=401.1,416.1
XS Rating Curve= 0 ,0
Exp/Cntr=0.3,0.1

Type RM Length L Ch R = 1 ,24373.9 ,302.8,327.7,355.2
XS GIS Cut Line= 3
     1933265.958      246737.555     1933516.088      246566.416
     1934051.979       245911.59
#Sta/Elev= 30
       0 2603.09     9.8 2601.28    29.3 2594.79    48.9 2591.59    97.8 2575.95
   107.5 2574.06   283.5 2570.75   303.1 2570.14     323 2567.44   332.9  2567.4
   353.8  2567.4   368.8  2567.4   402.6 2567.78   422.5 2571.15   432.5 2571.85
   502.2 2568.48   551.9 2568.55   671.4 2575.43   701.3 2580.27   711.2 2580.16
   810.8 2597.43   830.7 2599.21   840.6 2598.43   940.2 2612.18   960.1 2611.18
  1019.8 2621.98  1039.7 2624.72  1059.6 2626.16  1079.5 2622.84  1149.2 2624.62
#Mann= 3 , 0 , 0
       0      .1       0   353.8    .045       0   368.8      .1       0
#XS Ineff= 2 , 0
                          441.53         2571.69
Permanent Ineff=
       F       F
Bank Sta=353.8,368.8
XS Rating Curve= 0 ,0
Exp/Cntr=0.3,0.1

Type RM Length L Ch R = 1 ,24046.2 ,78.2,81.7,85.2
XS GIS Cut Line= 3
     1933378.825       246704.59     1933943.381      246812.206
     1934441.175      246269.027
#Sta/Elev= 30
       0 2574.09    79.3 2574.07   128.8 2577.06   138.7 2575.91   158.5 2569.05
   178.4 2565.19     218 2561.85   287.4  2560.6   297.3 2558.98   317.1 2551.62
   325.6 2550.86     327 2550.73   340.6 2552.22   406.3 2564.63   455.8 2571.17
   554.9 2575.81   604.6 2584.91   664.3 2586.83   704.2 2591.65   753.9 2594.65
   823.6 2594.19   843.6 2595.78   903.3 2593.55   943.1 2593.95     963 2595.97
  1032.7 2590.02  1082.5 2593.04  1152.2 2588.69    1202 2591.28  1311.5 2592.18
#Mann= 3 , 0 , 0
       0      .1       0   325.6    .045       0   340.6      .1       0
Bank Sta=325.6,340.6
XS Rating Curve= 0 ,0
Exp/Cntr=0.3,0.1

Type RM Length L Ch R = 1 ,23964.5 ,420,424.7,430.3
XS GIS Cut Line= 6
     1933320.396      246780.725     1933630.248       246826.76
     1933709.924      246855.089     1933761.271      246869.254
     1934009.153      246855.089     1934271.199      246892.272
#Sta/Elev= 30
       0 2584.54    29.4 2576.72    39.2 2574.84      49 2574.02    68.5 2574.72
   117.5 2578.19   195.8  2570.9   205.6 2569.13   225.2 2567.09   293.7 2563.92
   313.2 2560.97   350.8 2551.64   357.9 2550.95   360.2 2550.73   369.6  2551.4
   372.9 2552.54   388.4 2557.94   397.8  2559.8   451.1 2568.64   470.9 2570.94
     610 2573.87   659.6 2576.33   709.2 2582.19   777.8 2586.69   797.4 2590.22
   826.8    2597   856.2 2600.42     866 2600.86   934.6 2598.47     964 2599.64
#Mann= 3 , 0 , 0
       0      .1       0   357.9    .045       0   372.9      .1       0
Bank Sta=357.9,372.9
XS Rating Curve= 0 ,0
Exp/Cntr=0.3,0.1

Type RM Length L Ch R = 1 ,23539.5 ,272.7,279.3,285.9
XS GIS Cut Line= 2
     1933053.797      246931.798     1934065.811      247584.569
#Sta/Elev= 30
       0 2621.59    49.8 2612.55    69.7 2606.83    89.6 2596.22   109.5 2587.36
   139.3 2577.34   149.3 2575.98     199 2579.94     209 2579.82   278.7 2572.94
   318.5  2570.9   358.3 2563.55   378.2 2557.88   408.1 2551.25     418 2550.56
   428.7 2551.28   443.7 2553.78   527.5 2566.64   557.4 2566.04   567.3 2565.18
   587.2 2561.44   607.1 2560.89   766.4  2578.7   955.5 2584.88   975.4 2587.22
   995.3 2588.18    1045 2596.05  1074.9 2599.28  1174.4 2616.56  1204.3 2619.02
#Mann= 3 , 0 , 0
       0      .1       0   428.7    .045       0   443.7      .1       0
Bank Sta=428.7,443.7
XS Rating Curve= 0 ,0
Exp/Cntr=0.3,0.1

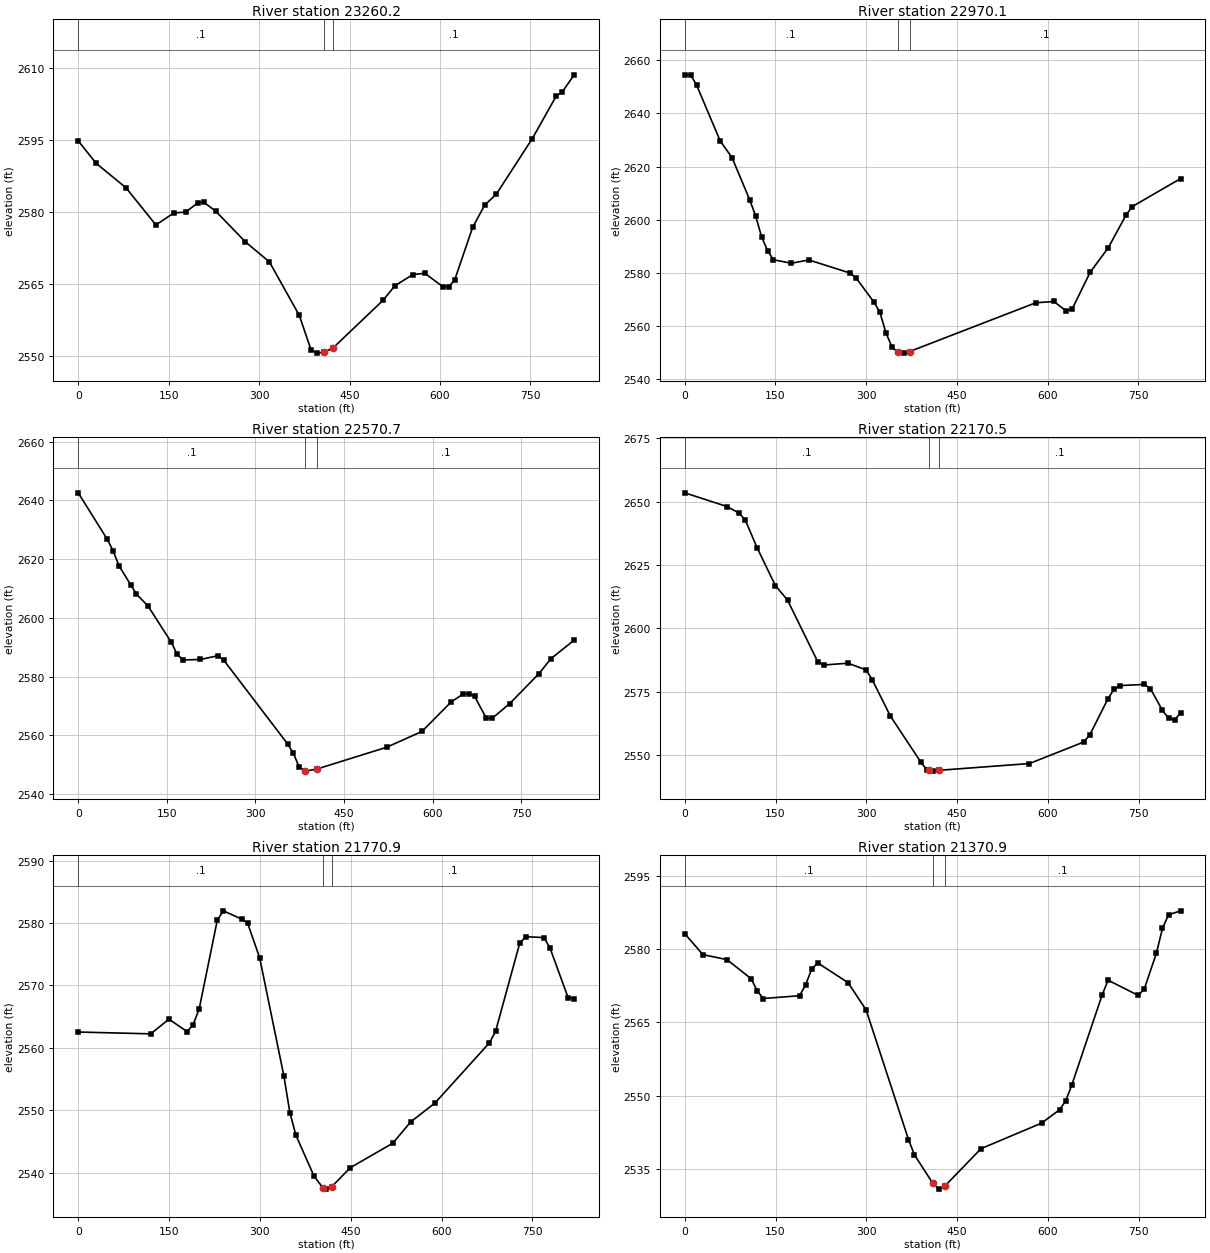
Type RM Length L Ch R = 1 ,23260.2 ,294,290,286
XS GIS Cut Line= 2
     1932954.945      247047.323     1933488.601      247673.098
#Sta/Elev= 30
       0 2594.85    29.7 2590.17    79.3 2585.04   128.8 2577.29   158.5 2579.78
   178.4 2579.99   198.2 2581.89   208.1 2582.04   227.9 2580.18   277.4 2573.74
   317.1 2569.57   366.6  2558.4   386.4 2551.08   396.4 2550.52     407 2550.72
     422 2551.53   505.4 2561.54   525.2  2564.6   554.9 2566.92   574.7  2567.2
   604.4 2564.42   614.3 2564.37   624.2 2565.78     654 2576.76   673.8 2581.38
   693.6 2583.77   753.1 2595.34   792.7 2604.21   802.6 2605.05   822.4 2608.64
#Mann= 3 , 0 , 0
       0      .1       0     407    .045       0     422      .1       0
Bank Sta=407,422
XS Rating Curve= 0 ,0
Exp/Cntr=0.3,0.1

Type RM Length L Ch R = 1 ,22970.1 ,397.3,399.2,400.2
XS GIS Cut Line= 3
     1932707.344        247310.8     1933025.013       247571.38
     1933341.222      247830.886
#Sta/Elev= 30
       0 2654.52     9.8 2654.46    19.6 2650.71    58.7 2629.65    78.3 2623.37
   107.6 2607.42   117.4 2601.38   127.2 2593.54     137  2588.4   146.7 2584.95
   176.1 2583.63   205.4 2584.86   273.9  2579.9   283.7    2578     313 2568.97
   322.8 2565.12   332.6 2557.54   342.4 2552.28   352.2 2550.05     362 2549.81
   371.7  2550.4   580.5 2568.76   610.4 2569.24   630.4 2565.73   640.4 2566.31
   670.3 2580.21   700.2 2589.42   730.1 2601.94   740.1 2604.97   819.9 2615.48
#Mann= 3 , 0 , 0
       0      .1       0   352.2    .045       0   371.7      .1       0
Bank Sta=352.2,371.7
XS Rating Curve= 0 ,0
Exp/Cntr=0.3,0.1

Type RM Length L Ch R = 1 ,22570.7 ,398.7,400,402.1
XS GIS Cut Line= 3
     1932433.169      247578.966     1932761.406      247846.306
     1933091.594      248099.627
#Sta/Elev= 30
       0  2642.6    49.2 2626.76    59.1  2622.8    68.9 2617.81    88.6 2611.34
    98.4 2608.14   118.1 2604.06   157.5 2591.73   167.4 2587.64   177.2 2585.68
   206.7 2585.84   236.3 2587.12   246.1 2585.67   354.4  2557.1   364.3 2553.89
   374.1 2549.16     384 2547.82   403.6 2548.51   522.4 2555.97   581.9 2561.34
   631.4  2571.4   651.2 2574.01   661.1 2574.18     671 2573.24   690.9 2565.83
   700.8 2565.82   730.5 2570.83     780 2581.04   799.9 2586.07   839.5 2592.42
#Mann= 3 , 0 , 0
       0      .1       0     384    .045       0   403.6      .1       0
Bank Sta=384,403.6
XS Rating Curve= 0 ,0
Exp/Cntr=0.3,0.1

Type RM Length L Ch R = 1 ,22170.5 ,404.4,399.6,394.7
XS GIS Cut Line= 3
     1932164.437      247814.986     1932461.926      248096.394
     1932759.415      248377.803
#Sta/Elev= 30
       0 2653.43    69.9 2648.03    89.9 2645.42    99.9 2642.79   119.8 2631.69
   149.8 2616.87   169.8 2611.17   219.7 2586.89   229.7 2585.58   269.7 2586.28
   299.6 2583.65   309.6 2579.82   339.6  2565.5   389.5 2547.47   399.5 2544.38
   404.2 2544.08   409.5 2543.75   419.2 2544.06   569.3 2546.74   659.2 2555.24
   669.2 2558.14   699.2 2572.36   709.1 2576.03   719.1 2577.47   759.1 2577.92
   769.1 2576.29     789 2567.67     799 2564.63     809 2563.96     819  2566.7
#Mann= 3 , 0 , 0
       0      .1       0   404.2    .045       0   419.2      .1       0
Bank Sta=404.2,419.2
XS Rating Curve= 0 ,0
Exp/Cntr=0.3,0.1

Type RM Length L Ch R = 1 ,21770.9 ,399.8,400,400.2
XS GIS Cut Line= 3
     1931865.702      248195.244      1932216.39      248406.687
     1932567.077      248618.131
#Sta/Elev= 30
       0 2562.52   119.8 2562.23   149.8 2564.58   179.8 2562.59   189.8  2563.7
   199.8 2566.24   229.7 2580.45   239.7 2581.94   269.7 2580.62   279.7 2579.98
   299.6 2574.43   339.6  2555.5   349.6 2549.58   359.6 2545.96   389.5 2539.42
   403.7 2537.61   409.5 2537.35   418.7 2537.74   449.4 2540.79   519.4  2544.7
   549.3 2548.14   589.3 2551.16   679.2  2560.8   689.2 2562.62   729.1 2576.75
   739.1 2577.79   769.1 2577.66     779 2576.02     809 2568.03     819 2567.88
#Mann= 3 , 0 , 0
       0      .1       0   403.7    .045       0   418.7      .1       0
Bank Sta=403.7,418.7
XS Rating Curve= 0 ,0
Exp/Cntr=0.3,0.1

Type RM Length L Ch R = 1 ,21370.9 ,405.4,399.6,394.3
XS GIS Cut Line= 3
     1931660.114      248533.432     1932008.869      248748.049
     1932357.623      248962.666
#Sta/Elev= 30
       0 2583.15      30 2578.86    69.9 2577.83   109.9 2573.91   119.8 2571.44
   129.8 2569.89   189.8 2570.46   199.8 2572.71   209.7 2575.88   219.7 2577.16
   269.7 2573.14   299.6 2567.57   369.6 2541.08   379.5 2537.95   409.5 2532.18
   419.5 2530.95   429.5 2531.56   489.4 2539.22   589.3 2544.43   619.2 2547.17
   629.2 2548.98   639.2 2552.18   689.2 2570.55   699.2 2573.63   749.1 2570.52
   759.1 2571.88     779 2579.15     789  2584.2     799 2586.99     819  2587.8
#Mann= 3 , 0 , 0
       0      .1       0   409.5    .045       0   429.5      .1       0
Bank Sta=409.5,429.5
XS Rating Curve= 0 ,0
Exp/Cntr=0.3,0.1

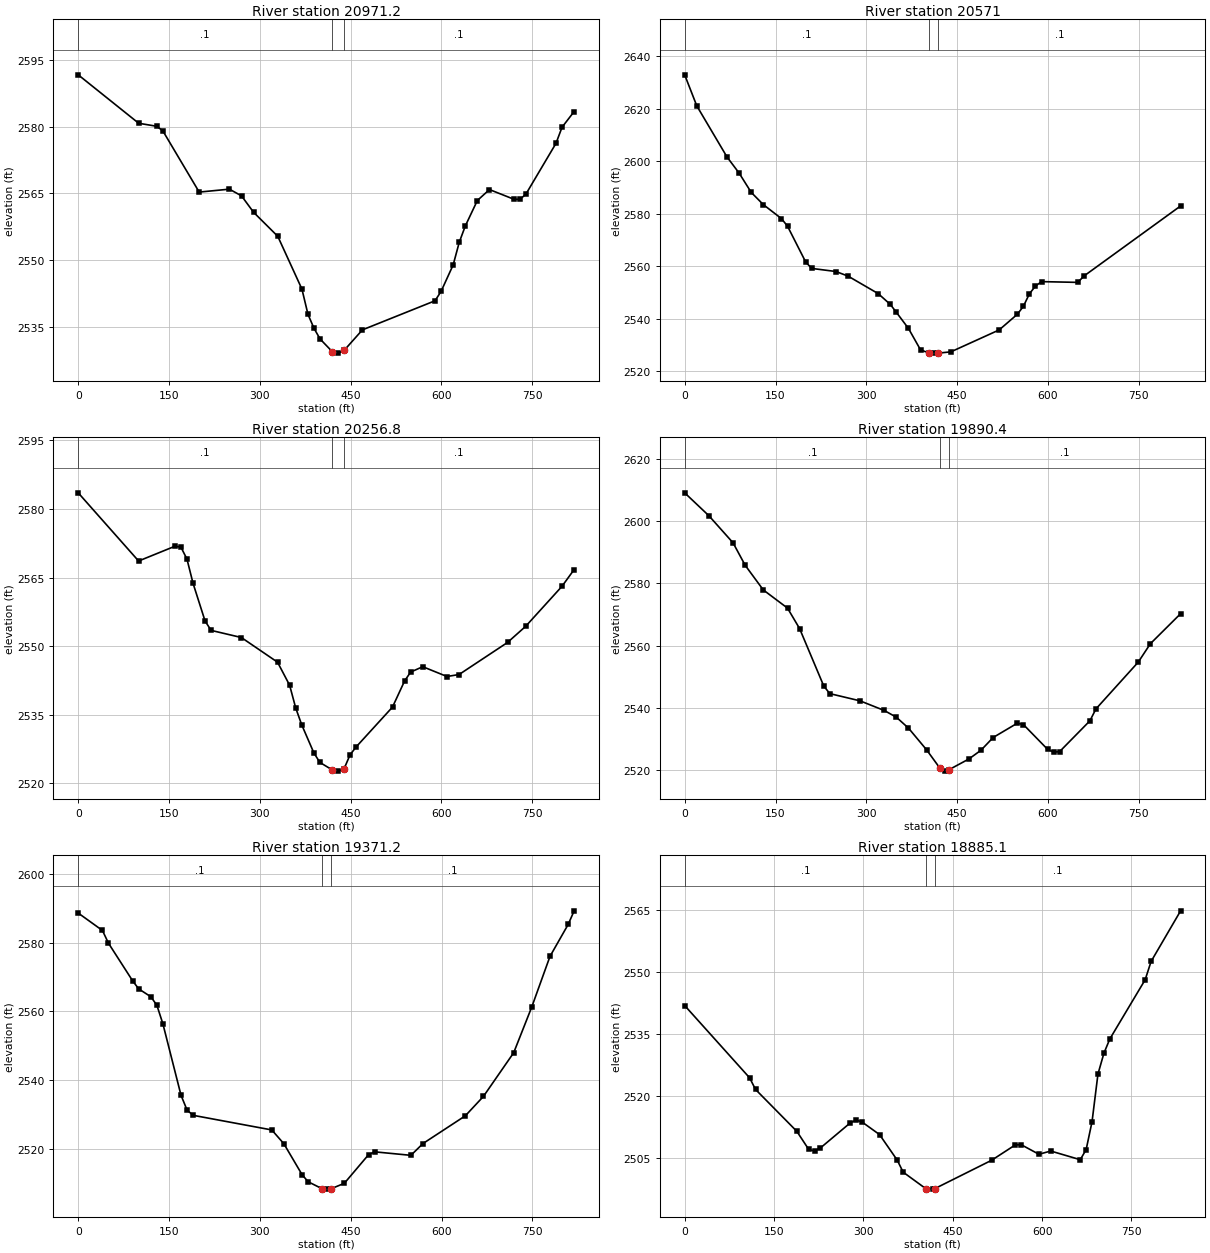
Type RM Length L Ch R = 1 ,20971.2 ,396.1,400.2,403.9
XS GIS Cut Line= 3
     1931412.503      248966.701     1931804.049      249086.563
      1932193.15       249214.54
#Sta/Elev= 30
       0 2591.71    99.9  2580.8   129.8 2580.12   139.8 2579.08   199.8  2565.3
   249.7 2565.96   269.7 2564.45   289.6 2560.76   329.6 2555.34   369.5 2543.45
   379.5 2537.75   389.5  2534.6   399.5 2532.21   419.5 2529.38   429.5 2529.03
   439.4 2529.68   469.4 2534.27   589.3 2540.82   599.3 2542.93   619.3 2548.91
   629.3 2553.98   639.3 2557.66   659.2  2563.4   679.2 2565.87   719.2 2563.71
   729.2 2563.64   739.2 2564.79   789.1 2576.28   799.1 2579.91   819.1 2583.45
#Mann= 3 , 0 , 0
       0      .1       0   419.5    .045       0   439.4      .1       0
Bank Sta=419.5,439.4
XS Rating Curve= 0 ,0
Exp/Cntr=0.3,0.1

Type RM Length L Ch R = 1 ,20571   ,315.9,314.2,312.4
XS GIS Cut Line= 3
     1931271.968      249254.661     1931634.968       249444.19
     1931997.968       249633.72
#Sta/Elev= 30
       0 2632.83      20 2621.01    69.9 2601.56    89.9 2595.42   109.9 2588.08
   129.8 2583.44   159.8  2578.1   169.8 2575.22   199.8  2561.6   209.7 2559.14
   249.7 2557.96   269.7 2556.22   319.6 2549.54   339.6 2545.43   349.6 2542.42
   369.6 2536.27   389.5 2528.13   403.5 2526.94   409.5 2526.89   418.5 2526.89
   439.5 2527.37   519.4 2535.73   549.3 2541.67   559.3 2544.68   569.3 2549.48
   579.3 2552.41   589.3 2554.11   649.2 2553.82   659.2 2556.21     819 2582.92
#Mann= 3 , 0 , 0
       0      .1       0   403.5    .045       0   418.5      .1       0
Bank Sta=403.5,418.5
XS Rating Curve= 0 ,0
Exp/Cntr=0.3,0.1

Type RM Length L Ch R = 1 ,20256.8 ,370.3,366.4,362.4
XS GIS Cut Line= 3
     1931124.942      249556.329     1931497.817      249725.157
     1931875.059      249886.336
#Sta/Elev= 30
       0 2583.51    99.8 2568.61   159.7 2571.83   169.7 2571.65   179.7 2569.04
   189.7 2563.77   209.6 2555.51   219.6 2553.45   269.6 2551.89   329.4  2546.5
   349.4 2541.46   359.4 2536.51   369.4  2532.8   389.4 2526.69   399.3  2524.6
   419.3    2523   429.3 2522.69   439.3 2523.18   449.3 2526.27   459.3 2527.98
   519.4 2536.69   539.4  2542.4   549.4 2544.34   569.4 2545.51   609.4 2543.37
   629.4  2543.8   709.5 2550.81   739.5 2554.34   799.5 2563.08   819.6 2566.75
#Mann= 3 , 0 , 0
       0      .1       0   419.3    .045       0   439.3      .1       0
Bank Sta=419.3,439.3
XS Rating Curve= 0 ,0
Exp/Cntr=0.3,0.1

Type RM Length L Ch R = 1 ,19890.4 ,517.3,519.2,520.9
XS GIS Cut Line= 3
      1930962.56      249973.274      1931360.95      250068.014
      1931759.34      250162.754
#Sta/Elev= 30
       0 2609.12      40 2601.75    79.9 2593.04    99.9 2585.82   129.8  2577.9
   169.8 2572.05   189.8 2565.46   229.7 2546.99   239.7 2544.55   289.6 2542.23
   329.6 2539.13   349.6 2536.96   369.6 2533.46   399.5 2526.48   421.6 2520.55
   429.5 2519.63   436.6  2520.1   469.4 2523.54   489.4 2526.36   509.4 2530.44
   549.3 2535.04   559.3 2534.62   599.3 2526.64   609.3 2525.74   619.2 2525.91
   669.2 2535.81   679.2 2539.64   749.1  2554.7   769.1 2560.61     819 2570.26
#Mann= 3 , 0 , 0
       0      .1       0   421.6    .045       0   436.6      .1       0
Bank Sta=421.6,436.6
XS Rating Curve= 0 ,0
Exp/Cntr=0.3,0.1

Type RM Length L Ch R = 1 ,19371.2 ,490.2,486,483.5
XS GIS Cut Line= 3
     1930847.765      250443.643     1931237.091      250570.835
     1931627.326      250694.882
#Sta/Elev= 30
       0 2588.64      40 2583.57      50 2579.85    89.9  2568.9    99.9 2566.56
   119.9 2564.28   129.9  2561.8   139.9 2556.35   169.8 2535.57   179.8 2531.26
   189.8 2529.75   319.7 2525.49   339.6 2521.48   369.6  2512.5   379.6 2510.42
     403 2508.35   409.6 2508.26     418  2508.4   439.5 2509.96   479.5 2518.29
   489.5 2519.12   549.4  2518.1   569.4 2521.54   639.3 2529.61   669.2 2535.26
   719.2 2547.99   749.1 2561.34   779.1 2576.03   809.1 2585.32     819 2589.29
#Mann= 3 , 0 , 0
       0      .1       0     403    .045       0     418      .1       0
Bank Sta=403,418
XS Rating Curve= 0 ,0
Exp/Cntr=0.3,0.1

Type RM Length L Ch R = 1 ,18885.1 ,286.9,287.2,285.8
XS GIS Cut Line= 2
     1930627.341      250909.722     1931442.267      251080.432
#Sta/Elev= 30
       0 2541.86     109 2524.35   118.9 2521.54   188.3 2511.38   208.2 2507.01
   218.1 2506.62     228 2507.37   277.5 2513.37   287.4 2514.11   297.4 2513.68
   327.1  2510.6   356.8 2504.41   366.8 2501.49   405.2 2497.45   416.3 2497.38
   420.2 2497.52   515.4 2504.38   555.1  2508.1     565 2508.14   594.7 2505.83
   614.6 2506.61   664.1 2504.51     674 2506.96   683.9 2513.72   693.8 2525.24
   703.8  2530.3   713.7 2533.75   773.1 2548.12     783 2552.54   832.6 2564.81
#Mann= 3 , 0 , 0
       0      .1       0   405.2    .045       0   420.2      .1       0
Bank Sta=405.2,420.2
XS Rating Curve= 0 ,0
Exp/Cntr=0.3,0.1