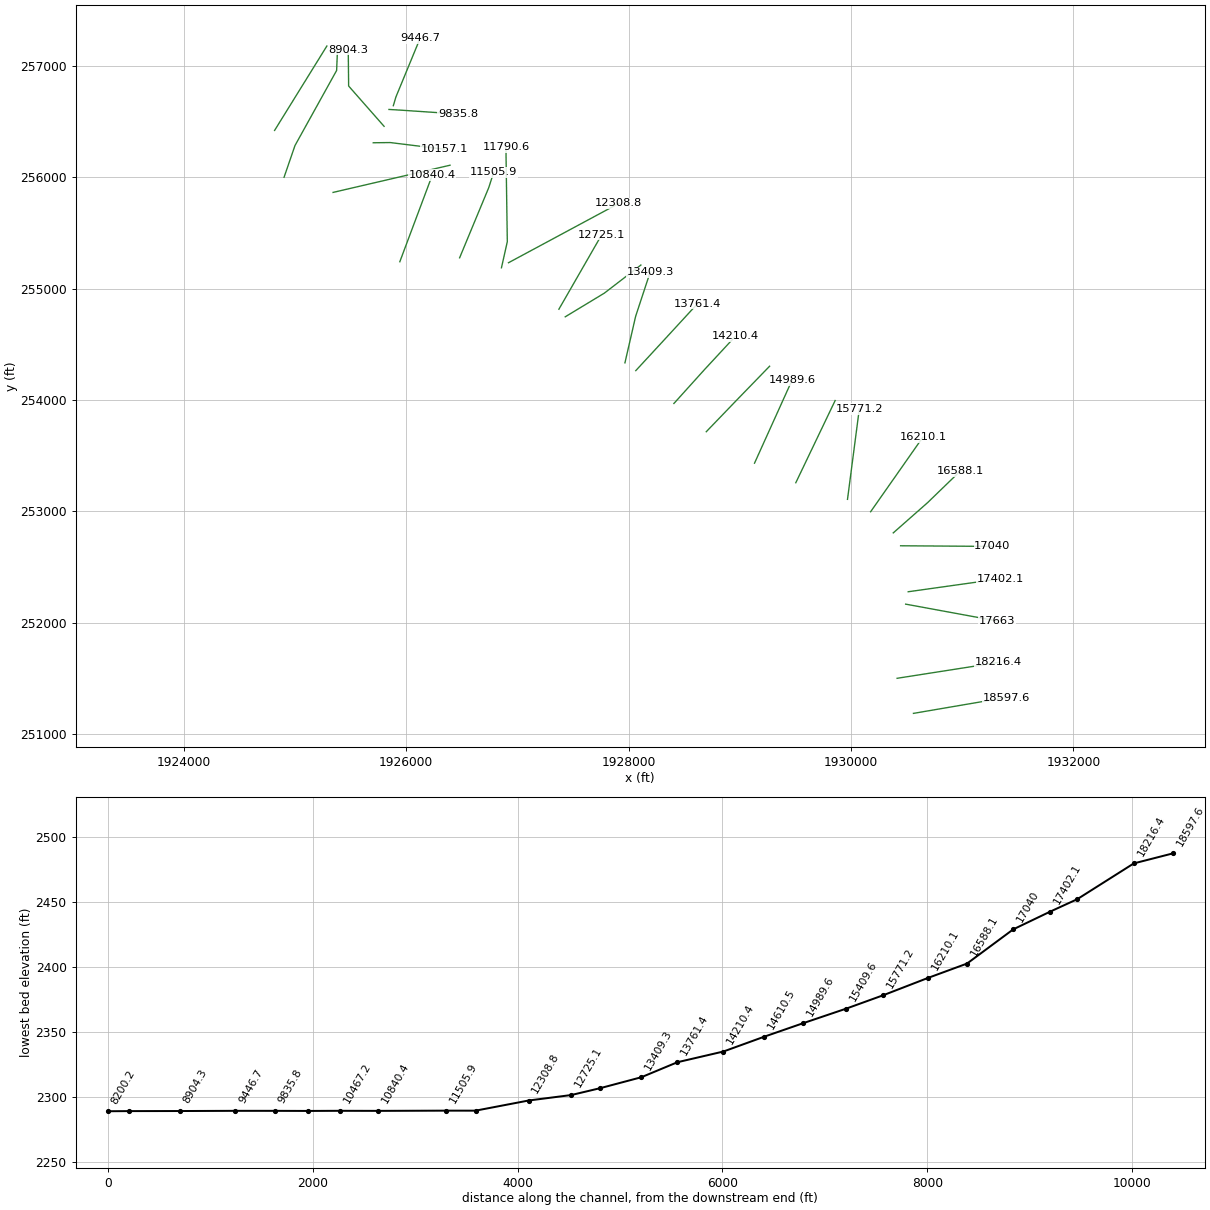
HEC-RAS study BvrCrk.prj: BvrCrk

--- BvrCrk.g01 (geometry) --- (continued)

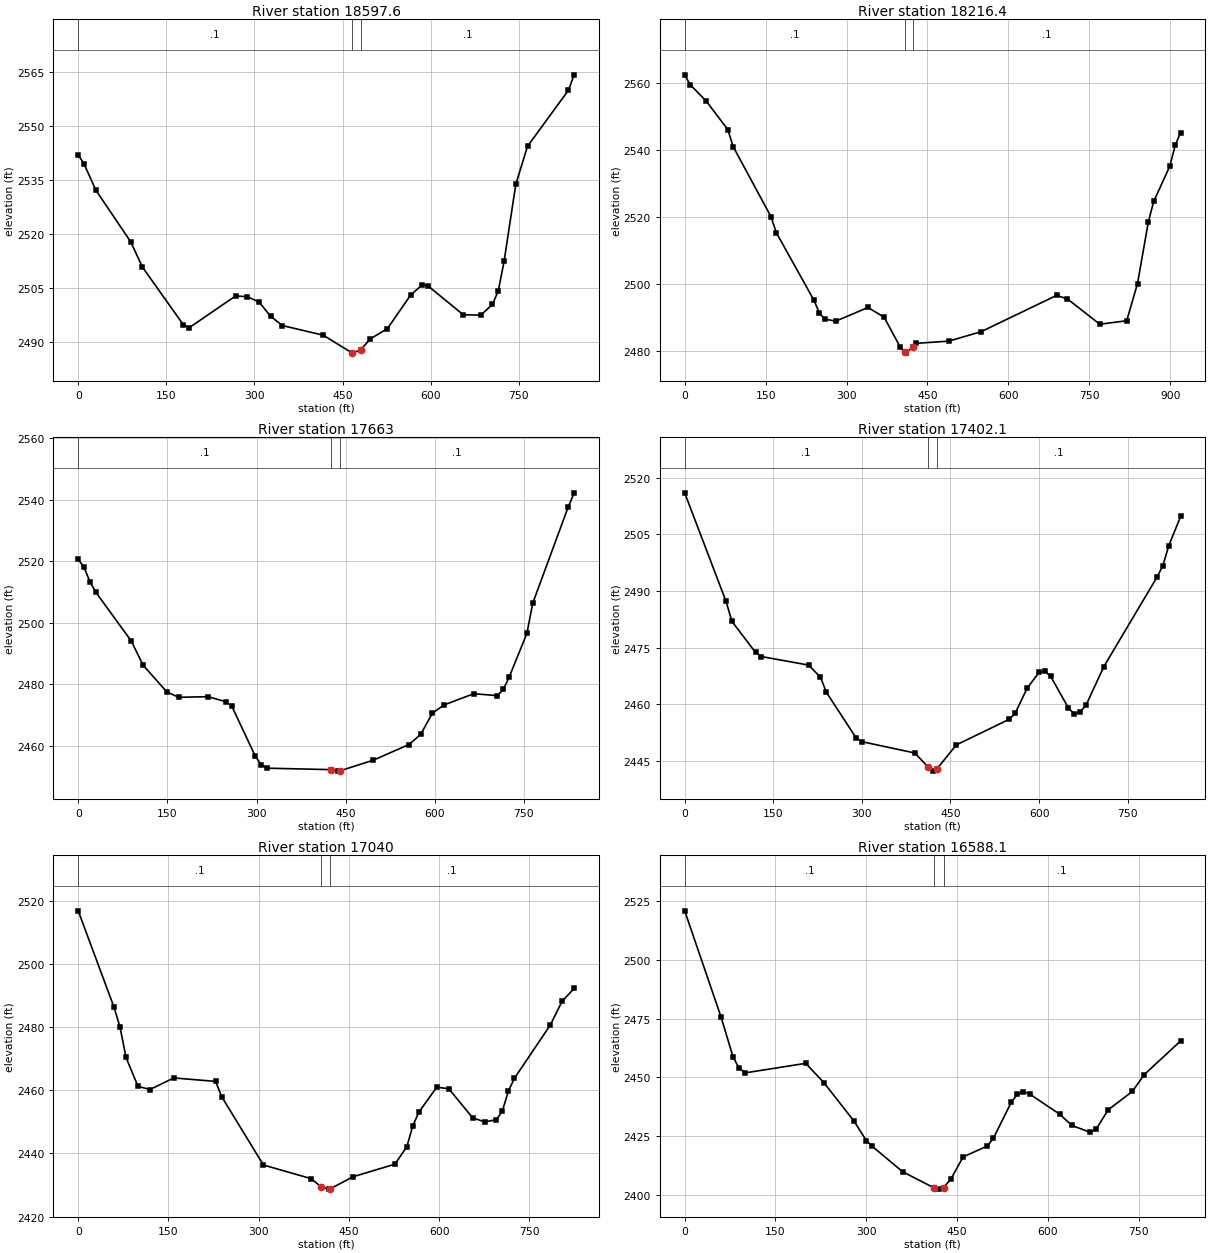
Type RM Length L Ch R = 1 ,18597.6 ,380.9,380.8,380.7
XS GIS Cut Line= 2
     1930561.949      251183.695     1931394.003      251325.809
#Sta/Elev= 30
       0 2541.95     9.9 2539.49    29.8 2532.25    89.4 2517.87   109.2  2510.9
   178.8 2494.91   188.7 2494.04   268.1  2502.9     288 2502.64   307.8  2501.2
   327.7 2497.19   347.6 2494.66   417.1 2491.99   466.3 2487.05   466.7 2487.02
   481.3 2487.97   496.5  2490.9   526.3 2493.82     566 2503.17   585.9    2506
   595.8 2505.59   655.4 2497.66   685.2 2497.56   705.1 2500.53     715 2504.33
   724.9  2512.5   744.8 2533.84   764.7 2544.36   834.2 2559.86   844.1 2564.17
#Mann= 3 , 0 , 0
       0      .1       0   466.3    .045       0   481.3      .1       0
Bank Sta=466.3,481.3
XS Rating Curve= 0 ,0
Exp/Cntr=0.3,0.1

Type RM Length L Ch R = 1 ,18216.4 ,560.1,553,545.8
XS GIS Cut Line= 2
     1930414.996      251498.957     1931323.179      251640.973
#Sta/Elev= 30
       0 2562.37      10 2559.46      40 2554.53    79.9 2546.04    89.9 2540.93
   159.9 2520.07   169.9 2515.27   239.8 2495.05   249.8 2491.25   259.8 2489.51
   279.8 2488.86   339.7 2492.96   369.7 2490.04   399.7 2481.09   407.6 2479.69
   409.6 2479.34   422.6 2481.11   429.6 2482.27   489.6 2482.92   549.5 2485.74
   689.4 2496.57   709.4 2495.51   769.4 2487.96   819.3    2489   839.3 2500.11
   859.3 2518.42   869.3  2524.6   899.2 2535.13   909.2 2541.38   919.2 2545.12
#Mann= 3 , 0 , 0
       0      .1       0   407.6    .045       0   422.6      .1       0
Bank Sta=407.6,422.6
XS Rating Curve= 0 ,0
Exp/Cntr=0.3,0.1

Type RM Length L Ch R = 1 ,17663   ,254.3,261.2,268
XS GIS Cut Line= 2
     1930491.833      252165.412     1931312.556      252014.566
#Sta/Elev= 30
       0 2520.68     9.9    2518    19.9  2513.3    29.8 2509.91    89.4 2494.05
   109.3 2486.22     149 2477.57   168.9  2475.8   218.6    2476   248.4 2474.36
   258.3 2472.98     298 2456.64     308 2453.86   317.9 2452.76   425.5 2452.28
   437.1  2451.8   440.5  2451.9   496.7 2455.37   556.3 2460.43   576.2 2463.72
     596 2470.65   615.9 2473.33   665.6 2476.97   705.3 2476.34   715.3 2478.34
   725.2 2482.37     755 2496.58   764.9 2506.43   824.5 2537.65   834.5 2542.26
#Mann= 3 , 0 , 0
       0      .1       0   425.5    .045       0   440.5      .1       0
Bank Sta=425.5,440.5
XS Rating Curve= 0 ,0
Exp/Cntr=0.3,0.1

Type RM Length L Ch R = 1 ,17402.1 ,365.6,362.3,359
XS GIS Cut Line= 2
     1930514.781       252276.76     1931346.197       252393.47
#Sta/Elev= 30
       0    2516      70 2487.28      80 2481.99   119.9 2473.77   129.9 2472.68
   209.9 2470.42   229.9  2467.2   239.9 2463.23   289.8 2451.26   299.8 2450.17
   389.8 2447.16   411.4 2443.55   419.8 2442.37   426.4 2442.83   459.8  2449.3
   549.7  2456.1   559.7 2457.77   579.7 2464.27   599.7 2468.47   609.7  2468.8
   619.7 2467.42   649.7 2459.06   659.7 2457.44   669.6 2458.01   679.6 2459.86
   709.6 2470.02   799.6 2493.68   809.6 2496.76   819.6 2502.03   839.6 2509.75
#Mann= 3 , 0 , 0
       0      .1       0   411.4    .045       0   426.4      .1       0
Bank Sta=411.4,426.4
XS Rating Curve= 0 ,0
Exp/Cntr=0.3,0.1

Type RM Length L Ch R = 1 ,17040   ,434.6,451.7,469.3
XS GIS Cut Line= 2
     1930446.318      252689.909      1931270.75      252684.161
#Sta/Elev= 30
       0 2516.76    59.6 2486.21    69.5 2479.93    79.5 2470.35    99.3 2461.23
   119.2  2460.2   158.9 2463.87   228.5 2462.77   238.4 2457.96   307.9 2436.32
   387.4 2431.98   404.1 2429.34   417.2 2428.68   419.1 2428.79   456.9  2432.6
   526.5 2436.58   546.3 2442.14   556.3 2448.72   566.2 2453.03     596 2460.93
   615.9 2460.47   655.6 2451.27   675.5 2449.97   695.3 2450.64   705.2  2453.5
   715.2 2459.78   725.1 2463.76   784.7 2480.59   804.6 2488.21   824.4 2492.18
#Mann= 3 , 0 , 0
       0      .1       0   404.1    .045       0   419.1      .1       0
Bank Sta=404.1,419.1
XS Rating Curve= 0 ,0
Exp/Cntr=0.3,0.1

Type RM Length L Ch R = 1 ,16588.1 ,373.2,378,382.4
XS GIS Cut Line= 3
     1930380.163      252805.706     1930688.048      253076.534
     1930982.404      253361.078
#Sta/Elev= 30
       0 2520.97      60 2475.79      80 2458.64      90  2453.9     100 2451.91
     200 2455.97     230 2447.74     280 2431.27     300 2423.08     310 2420.58
     360 2409.79   412.7  2402.8     420 2402.36   427.7 2402.99     440 2406.73
     460 2416.08   499.9 2420.73   509.9 2423.96   539.9 2439.54   549.8 2442.76
   559.8 2443.91   569.8 2442.92   619.7 2434.27   639.7  2429.5   669.7  2426.6
   679.7 2427.83   699.6 2436.13   739.6 2443.99   759.5 2451.21   819.4 2465.52
#Mann= 3 , 0 , 0
       0      .1       0   412.7    .045       0   427.7      .1       0
Bank Sta=412.7,427.7
XS Rating Curve= 0 ,0
Exp/Cntr=0.3,0.1

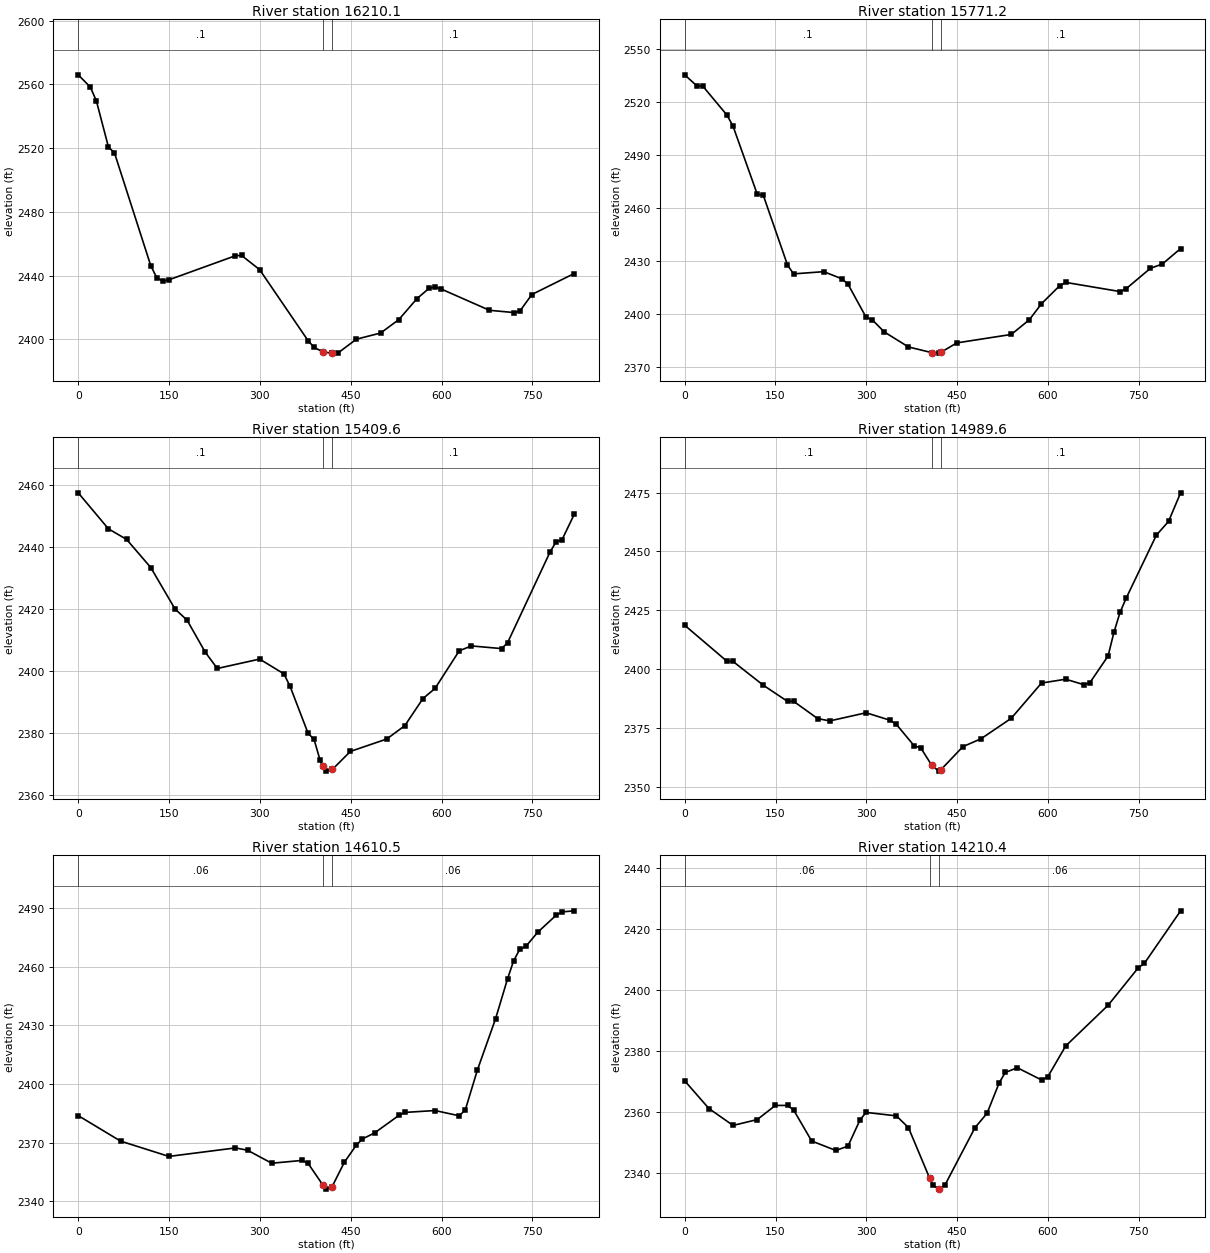
Type RM Length L Ch R = 1 ,16210.1 ,427.9,438.8,449.7
XS GIS Cut Line= 3
     1930176.663      252995.639     1930411.788       253330.91
     1930646.913       253666.18
#Sta/Elev= 30
       0 2566.04      20 2558.35      30 2549.68    49.9 2520.77    59.9 2517.04
   119.8 2446.31   129.8 2438.63   139.8 2436.66   149.8 2437.43   259.7 2452.54
   269.7 2452.73   299.6  2443.8   379.5 2399.29   389.5 2395.02   404.7  2392.1
   419.5 2391.42   419.7 2391.42   429.5 2391.66   459.4 2400.17   499.4 2404.04
   529.4 2412.42   559.3 2425.58   579.3 2432.05   589.3 2432.94   599.3 2431.66
   679.2 2418.29   719.1 2416.89   729.1 2417.64   749.1 2428.19     819 2441.36
#Mann= 3 , 0 , 0
       0      .1       0   404.7    .045       0   419.7      .1       0
Bank Sta=404.7,419.7
XS Rating Curve= 0 ,0
Exp/Cntr=0.3,0.1

Type RM Length L Ch R = 1 ,15771.2 ,368.8,361.6,354.5
XS GIS Cut Line= 2
     1929968.704      253107.146     1930074.919      253919.712
#Sta/Elev= 30
       0 2535.22      20 2529.02      30 2528.82      70 2512.42      80 2506.14
   119.9  2467.8   129.9 2467.18   169.9 2427.83   179.9 2422.81   229.8 2424.06
   259.8 2420.03   269.8 2417.01   299.8  2398.3   309.8 2396.91   329.8 2390.03
   369.8 2381.54   408.1 2378.36   419.7 2378.06   423.1 2378.47   449.7 2383.84
   539.7 2388.61   569.6 2396.93   589.6 2405.96   619.6  2416.1   629.6    2418
   719.5 2412.82   729.5 2414.43   769.5 2425.93   789.5 2428.42   819.5 2437.12
#Mann= 3 , 0 , 0
       0      .1       0   408.1    .045       0   423.1      .1       0
Bank Sta=408.1,423.1
XS Rating Curve= 0 ,0
Exp/Cntr=0.3,0.1

Type RM Length L Ch R = 1 ,15409.6 ,419.5,420,420.5
XS GIS Cut Line= 3
     1929503.881      253256.644     1929680.782      253625.962
     1929857.683      253995.281
#Sta/Elev= 30
       0 2457.53    49.9 2445.92    79.9  2442.5   119.8 2433.44   159.8 2420.08
   179.8 2416.45   209.7 2406.15   229.7 2400.87   299.6  2403.9   339.6 2399.15
   349.6 2395.25   379.5 2380.01   389.5 2377.98   399.5 2371.23   404.9 2369.36
   409.5 2367.76   419.9 2368.34   449.4 2374.11   509.4 2378.11   539.3 2382.42
   569.3 2391.16   589.3 2394.44   629.2 2406.56   649.2 2408.15   699.2 2407.28
   709.1  2409.2     779 2438.36     789 2441.68     799 2442.41     819 2450.54
#Mann= 3 , 0 , 0
       0      .1       0   404.9    .045       0   419.9      .1       0
Bank Sta=404.9,419.9
XS Rating Curve= 0 ,0
Exp/Cntr=0.3,0.1

Type RM Length L Ch R = 1 ,14989.6 ,386.9,379.1,371.3
XS GIS Cut Line= 3
     1929132.412      253432.246     1929301.272      253805.309
     1929470.133      254178.373
#Sta/Elev= 30
       0 2418.62    69.9 2403.28    79.9 2403.21   129.8 2393.12   169.8 2386.24
   179.8 2386.27   219.7 2378.91   239.7 2377.94   299.6  2381.4   339.6 2378.18
   349.6 2376.44   379.5  2367.2   389.5  2366.6   408.2    2359   419.5 2356.58
   423.2 2357.18   459.4 2366.98   489.4 2370.34   539.3 2379.05   589.3 2394.04
   629.2 2395.67   659.2 2393.34   669.2  2394.2   699.2 2405.54   709.1 2415.84
   719.1 2424.18   729.1 2430.15     779 2456.94     799 2462.76     819 2474.93
#Mann= 3 , 0 , 0
       0      .1       0   408.2    .045       0   423.2      .1       0
Bank Sta=408.2,423.2
XS Rating Curve= 0 ,0
Exp/Cntr=0.3,0.1

Type RM Length L Ch R = 1 ,14610.5 ,399.3,400,400.6
XS GIS Cut Line= 3
     1928698.532      253714.985      1928982.74      254009.806
     1929268.072      254303.533
#Sta/Elev= 30
       0 2383.85    69.9  2370.8   149.8 2362.96   259.7 2367.31   279.7 2366.11
   319.6 2359.47   369.6 2360.91   379.5 2359.44   404.3  2348.2   409.5 2346.22
   419.3  2347.5   439.5 2359.96   459.4  2368.8   469.4 2371.91   489.4 2374.98
   529.4 2383.91   539.3 2385.47   589.3 2386.44   629.2 2383.75   639.2 2386.73
   659.2 2407.18   689.2 2433.38   709.1 2453.95   719.1  2463.1   729.1 2468.92
   739.1 2470.39   759.1 2477.76     789 2486.32     799 2488.09     819 2488.64
#Mann= 3 , 0 , 0
       0     .06       0   404.3    .045       0   419.3     .06       0
Bank Sta=404.3,419.3
XS Rating Curve= 0 ,0
Exp/Cntr=0.3,0.1

Type RM Length L Ch R = 1 ,14210.4 ,449.2,449.1,449.2
XS GIS Cut Line= 3
     1928407.417       253968.63     1928681.893      254272.516
     1928960.407      254572.776
#Sta/Elev= 30
       0 2370.33      40 2361.24    79.9 2355.69   119.8 2357.61   149.8 2362.25
   169.8 2362.25   179.8 2360.79   209.7 2350.58   249.7 2347.47   269.7 2348.92
   289.6 2357.52   299.6 2359.96   349.6 2358.83   369.5 2354.98   404.4 2338.45
   409.5 2336.19   419.4 2334.79   429.5 2336.01   479.4 2354.95   499.4 2359.69
   519.4 2369.67   529.4 2373.06   549.3 2374.62   589.3 2370.61   599.3 2371.52
   629.2 2381.76   699.2 2395.11   749.1 2407.41   759.1 2408.85     819  2426.1
#Mann= 3 , 0 , 0
       0     .06       0   404.4    .045       0   419.4     .06       0
Bank Sta=404.4,419.4
XS Rating Curve= 0 ,0
Exp/Cntr=0.3,0.1

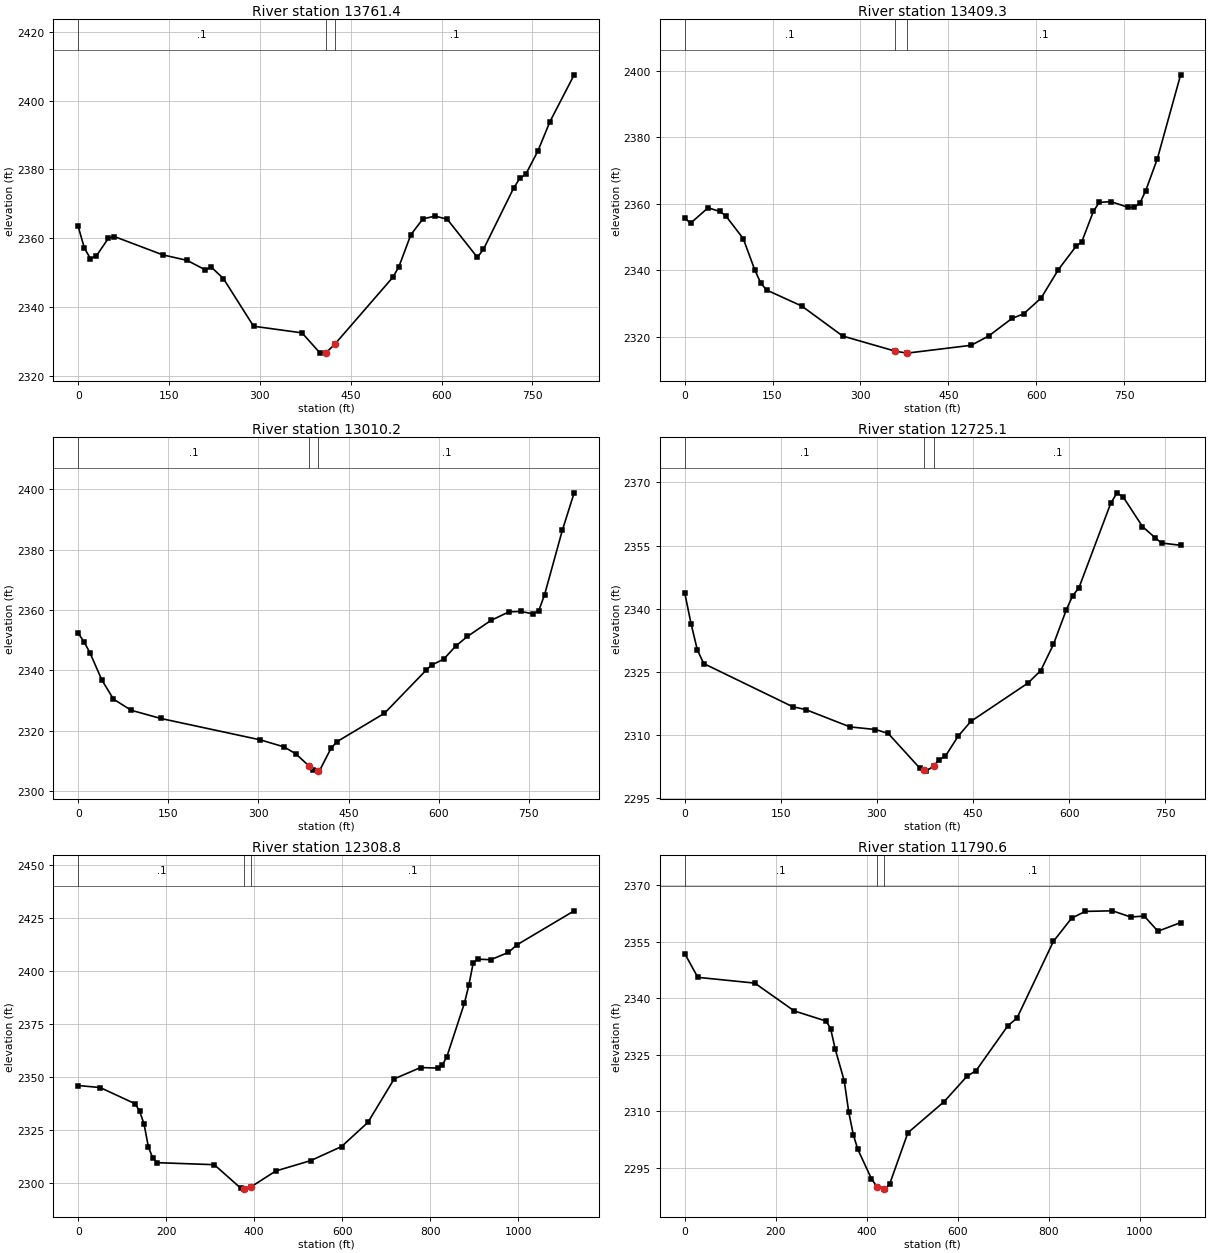
Type RM Length L Ch R = 1 ,13761.4 ,340.3,352.1,362
XS GIS Cut Line= 3
     1928064.615      254263.849     1928342.561      254564.575
     1928619.881       254865.88
#Sta/Elev= 30
       0 2363.38      10 2357.17      20 2354.07      30 2354.82    49.9 2359.98
    59.9 2360.44   139.8 2355.12   179.8 2353.53   209.7 2350.78   219.7 2351.58
   239.7 2348.25   289.6 2334.38   369.6 2332.45   399.5 2326.56   408.7  2326.6
   423.7 2329.14   519.4 2348.57   529.4 2351.59   549.3 2360.98   569.3  2365.6
   589.3 2366.39   609.3 2365.51   659.2  2354.4   669.2 2356.74   719.1 2374.55
   729.1 2377.34   739.1 2378.57   759.1 2385.31     779 2393.85     819 2407.47
#Mann= 3 , 0 , 0
       0      .1       0   408.7    .045       0   423.7      .1       0
Bank Sta=408.7,423.7
XS Rating Curve= 0 ,0
Exp/Cntr=0.3,0.1

Type RM Length L Ch R = 1 ,13409.3 ,417.3,398.7,382.4
XS GIS Cut Line= 3
     1927967.031      254333.939     1928063.335      254752.488
     1928193.955      255148.379
#Sta/Elev= 30
       0 2355.72      10 2354.15      40  2358.8    59.9 2357.69    69.9 2356.42
    99.9 2349.53   119.9 2339.96   129.8 2336.14   139.8 2334.02   199.8 2329.21
   269.7 2320.17   359.6  2315.6   379.6 2315.02     489 2317.38   518.8 2320.18
   558.5 2325.46   578.4 2326.85   608.2 2331.59   637.9  2340.2   667.7 2347.15
   677.6  2348.5   697.5  2357.7   707.4  2360.4   727.3 2360.66     757 2358.92
     767 2358.92   776.9 2360.21   786.8 2363.93   806.7 2373.57   846.4 2398.84
#Mann= 3 , 0 , 0
       0      .1       0   359.6    .045       0   379.6      .1       0
Bank Sta=359.6,379.6
XS Rating Curve= 0 ,0
Exp/Cntr=0.3,0.1

Type RM Length L Ch R = 1 ,13010.2 ,273.6,285.1,296.1
XS GIS Cut Line= 3
     1927430.136      254747.656     1927781.928      254960.333
      1928110.52      255212.831
#Sta/Elev= 30
       0 2352.38     9.8 2349.43    19.6 2345.86    39.2  2336.9    58.7 2330.52
    88.1 2326.84     137 2324.14   303.4 2317.02   342.6  2314.7   362.1 2312.42
   384.8 2308.27   391.5 2307.02   399.8 2306.73   401.3 2306.68     421 2314.31
   430.8 2316.44   509.8 2325.84   578.8 2340.04   588.7 2341.84   608.4 2343.76
   628.2 2348.05   647.9 2351.29   687.4 2356.62     717 2359.42   736.7 2359.56
   756.4 2358.77   766.3 2359.64   776.2 2365.05   805.8  2386.4   825.5 2398.83
#Mann= 3 , 0 , 0
       0      .1       0   384.8    .045       0   399.8      .1       0
Bank Sta=384.8,399.8
XS Rating Curve= 0 ,0
Exp/Cntr=0.3,0.1

Type RM Length L Ch R = 1 ,12725.1 ,429,416.2,403.3
XS GIS Cut Line= 2
     1927373.011      254815.627     1927758.998      255486.677
#Sta/Elev= 30
       0 2343.79     9.9 2336.45    19.8 2330.14    29.8 2326.92   168.7 2316.66
   188.6    2316     258 2311.87   297.8 2311.24   317.6 2310.32   367.2 2302.03
     374 2301.57   377.2 2301.35     389 2302.61     397 2304.06   406.9 2304.89
   426.8 2309.65   446.6 2313.17   535.9  2322.3   555.8 2325.27   575.6  2331.5
   595.5 2339.62   605.4 2343.01   615.3 2344.92     665 2365.04   674.9 2367.53
   684.8 2366.47   714.6  2359.5   734.4 2356.84   744.4 2355.59   774.1 2355.06
#Mann= 3 , 0 , 0
       0      .1       0     374    .045       0     389      .1       0
Bank Sta=374,389
XS Rating Curve= 0 ,0
Exp/Cntr=0.3,0.1

Type RM Length L Ch R = 1 ,12308.8 ,483.5,518.1,546.5
XS GIS Cut Line= 2
     1926919.742      255233.484     1927912.542      255766.986
#Sta/Elev= 30
       0 2346.07    49.9 2345.11   129.7 2337.42   139.6 2333.88   149.6 2327.92
   159.6 2316.94   169.6 2311.78   179.5 2309.64   309.2 2308.68     369 2297.66
   377.7 2297.21     379 2297.14   392.7 2298.21   448.8 2305.69   528.6 2310.62
   598.4 2317.24   658.3 2328.64   718.1  2349.2     778 2354.56   817.9  2354.3
   827.8 2355.79   837.8 2359.69   877.7 2384.96   887.7 2393.36   897.7    2404
   907.6 2405.74   937.6 2405.49   977.4 2408.91   997.4 2412.54  1127.1 2428.57
#Mann= 3 , 0 , 0
       0      .1       0   377.7    .045       0   392.7      .1       0
Bank Sta=377.7,392.7
XS Rating Curve= 0 ,0
Exp/Cntr=0.3,0.1

Type RM Length L Ch R = 1 ,11790.6 ,294.5,284.7,274.9
XS GIS Cut Line= 3
     1926856.408      255187.954     1926909.118      255422.936
     1926896.525      256272.362
#Sta/Elev= 30
       0 2351.86    28.9 2345.54   154.1 2344.01   240.8 2336.63   310.8 2333.94
   320.8 2331.96   330.8 2326.56   350.8 2318.06   360.8 2309.69   370.8 2303.76
   380.7 2299.87   410.7 2292.07   423.2 2289.89   438.2 2289.35   440.7 2289.34
   450.7 2290.71   490.7 2304.29   570.6 2312.58   620.6 2319.28   640.6 2320.78
   710.6 2332.71   730.5 2334.71   810.5 2355.06   850.5 2361.22   880.5 2363.04
   940.4 2363.19   980.4 2361.56  1010.4 2361.79  1040.4 2357.78  1090.3 2360.06
#Mann= 3 , 0 , 0
       0      .1       0   423.2    .045       0   438.2      .1       0
Bank Sta=423.2,438.2
XS Rating Curve= 0 ,0
Exp/Cntr=0.3,0.1

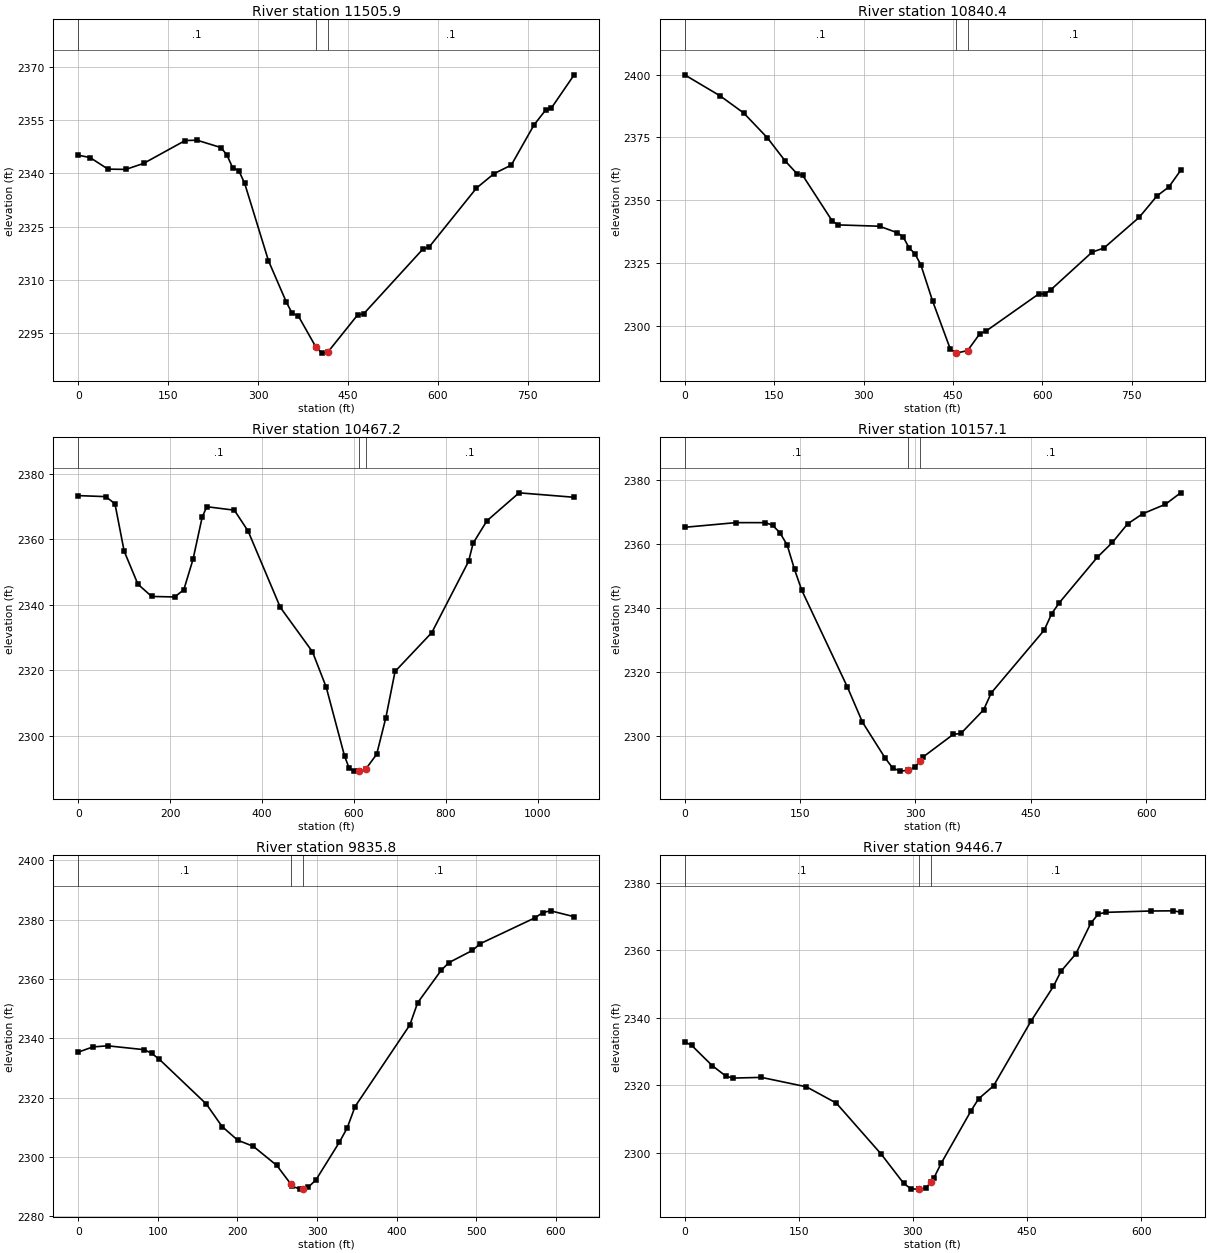
Type RM Length L Ch R = 1 ,11505.9 ,664.9,665.3,665.6
XS GIS Cut Line= 3
     1926480.175      255277.914     1926742.684      255909.846
     1926786.619      256045.908
#Sta/Elev= 30
       0  2345.1    19.8 2344.44    49.6 2341.18    79.3  2341.1   109.1 2342.79
   178.5 2349.24   198.3 2349.32     238 2347.26   247.9 2345.21   257.8 2341.51
   267.8 2340.77   277.7 2337.16   317.4 2315.35   347.1 2303.76     357 2300.52
   366.9  2299.9   396.7    2291   406.6 2289.35   416.5 2289.65   466.1 2300.11
     476 2300.38   575.2  2318.7   585.1 2319.18   664.4 2335.85   693.8 2339.92
   722.4 2342.31   760.5 2353.67   779.6 2357.78   789.1 2358.33   827.3 2367.74
#Mann= 3 , 0 , 0
       0      .1       0   396.7    .045       0   416.5      .1       0
Bank Sta=396.7,416.5
XS Rating Curve= 0 ,0
Exp/Cntr=0.3,0.1

Type RM Length L Ch R = 1 ,10840.4 ,395.4,373,350.6
XS GIS Cut Line= 2
      1925942.38      255242.337     1926234.526      256021.393
#Sta/Elev= 30
       0 2399.87    59.4 2391.51      99  2384.7   138.7 2374.82   168.4 2365.67
   188.2  2360.6   198.1 2359.83   247.6 2341.72   257.5 2340.18   326.9 2339.65
   356.6 2337.07   366.5  2335.4   376.4  2331.1   386.3 2328.67   396.2 2324.29
     416 2309.85   445.7 2290.75   455.6 2289.18   474.7  2290.2   495.3 2296.95
   505.2 2297.89   594.3 2312.78   604.2 2312.74   614.1 2314.34   683.5 2329.35
   703.3 2330.97   762.7 2343.24   792.4 2351.72   812.2 2355.26     832 2361.84
#Mann= 3 , 0 , 0
       0      .1       0   455.6    .045       0   474.7      .1       0
Bank Sta=455.6,474.7
XS Rating Curve= 0 ,0
Exp/Cntr=0.3,0.1

Type RM Length L Ch R = 1 ,10467.2 ,317.3,310,302.5
XS GIS Cut Line= 2
     1925342.153      255865.582     1926393.879      256109.922
#Sta/Elev= 30
       0 2373.35      60 2373.04      80 2370.85     100  2356.4     130 2346.29
     160 2342.56     210 2342.41   229.9 2344.61   249.9 2353.87   269.9 2366.77
   279.9 2369.96   339.9  2368.9   369.9 2362.51   439.9 2339.24   509.9 2325.69
   539.9 2314.87   579.9  2293.8   589.9 2290.13   599.8 2289.23   610.6  2289.3
   625.6 2289.78   649.8 2294.39   669.8 2305.59   689.8 2319.66   769.8 2331.53
   849.8 2353.26   859.8 2358.84   889.8 2365.66   959.8  2374.2  1079.7 2372.84
#Mann= 3 , 0 , 0
       0      .1       0   610.6    .045       0   625.6      .1       0
Bank Sta=610.6,625.6
XS Rating Curve= 0 ,0
Exp/Cntr=0.3,0.1

Type RM Length L Ch R = 1 ,10157.1 ,320.1,321.1,322.3
XS GIS Cut Line= 3
     1925703.352      256311.768     1925855.622      256313.539
     1926344.303      256253.339
#Sta/Elev= 30
       0 2365.31    66.6 2366.77   104.7 2366.76   114.2 2365.97   123.7 2363.63
   133.2  2359.8   142.8 2352.13   152.3 2345.59   211.4 2315.46   231.1 2304.43
   260.6 2293.21   270.4  2290.1   280.3 2289.13   290.9 2289.41     300 2290.54
   305.9 2292.34   309.8 2293.53   349.2 2300.62   359.1  2300.9   388.6 2308.27
   398.5 2313.55   467.4 2333.19   477.2 2338.36   487.1 2341.76   536.3 2355.93
     556 2360.57   575.7 2366.36   595.4 2369.54     625 2372.51   644.7 2376.08
#Mann= 3 , 0 , 0
       0      .1       0   290.9    .045       0   305.9      .1       0
Bank Sta=290.9,305.9
XS Rating Curve= 0 ,0
Exp/Cntr=0.3,0.1

Type RM Length L Ch R = 1 ,9835.8  ,361.5,389.4,417.3
XS GIS Cut Line= 3
     1925844.998      256610.997     1925937.069      256605.685
     1926466.602      256570.029
#Sta/Elev= 30
       0 2335.34    18.4 2337.09    36.9 2337.47      83 2336.16    92.2 2334.94
     102  2332.9     161 2317.84   180.7 2310.29   200.3 2305.69     220 2303.61
   249.5 2297.17   266.9 2290.97   269.1 2290.12     279  2289.2   281.9 2289.38
   288.8  2289.8   298.6  2292.3   328.1 2305.01   337.9 2309.81   347.8 2317.01
   416.6  2344.5   426.4 2351.97   455.9 2362.87   465.7 2365.49   495.2  2369.6
     505 2371.86   573.8 2380.58   583.6 2382.35   593.5 2382.93     623 2380.95
#Mann= 3 , 0 , 0
       0      .1       0   266.9    .045       0   281.9      .1       0
Bank Sta=266.9,281.9
XS Rating Curve= 0 ,0
Exp/Cntr=0.3,0.1

Type RM Length L Ch R = 1 ,9446.7  ,516.7,542.1,567.4
XS GIS Cut Line= 3
     1925883.951      256644.638     1925906.969      256722.543
      1926124.75      257250.177
#Sta/Elev= 30
       0 2332.83       9 2331.84    36.1 2325.82    54.2 2322.69    63.2 2322.11
   100.9 2322.32     160 2319.53   199.3 2314.71   258.4 2299.57   287.9 2290.92
   297.8 2289.26   307.6 2289.21   308.7 2289.25   317.4 2289.58   323.7 2291.36
   327.3 2292.37   337.1 2296.82   376.5 2312.43   386.3 2315.96     406 2319.79
   455.2 2338.95   484.7 2349.26   494.6 2353.72   514.3 2358.94     534 2368.04
   543.8 2370.72   553.6 2371.22   612.7 2371.62   642.2 2371.67     652 2371.29
#Mann= 3 , 0 , 0
       0      .1       0   308.7    .045       0   323.7      .1       0
Bank Sta=308.7,323.7
XS Rating Curve= 0 ,0
Exp/Cntr=0.3,0.1

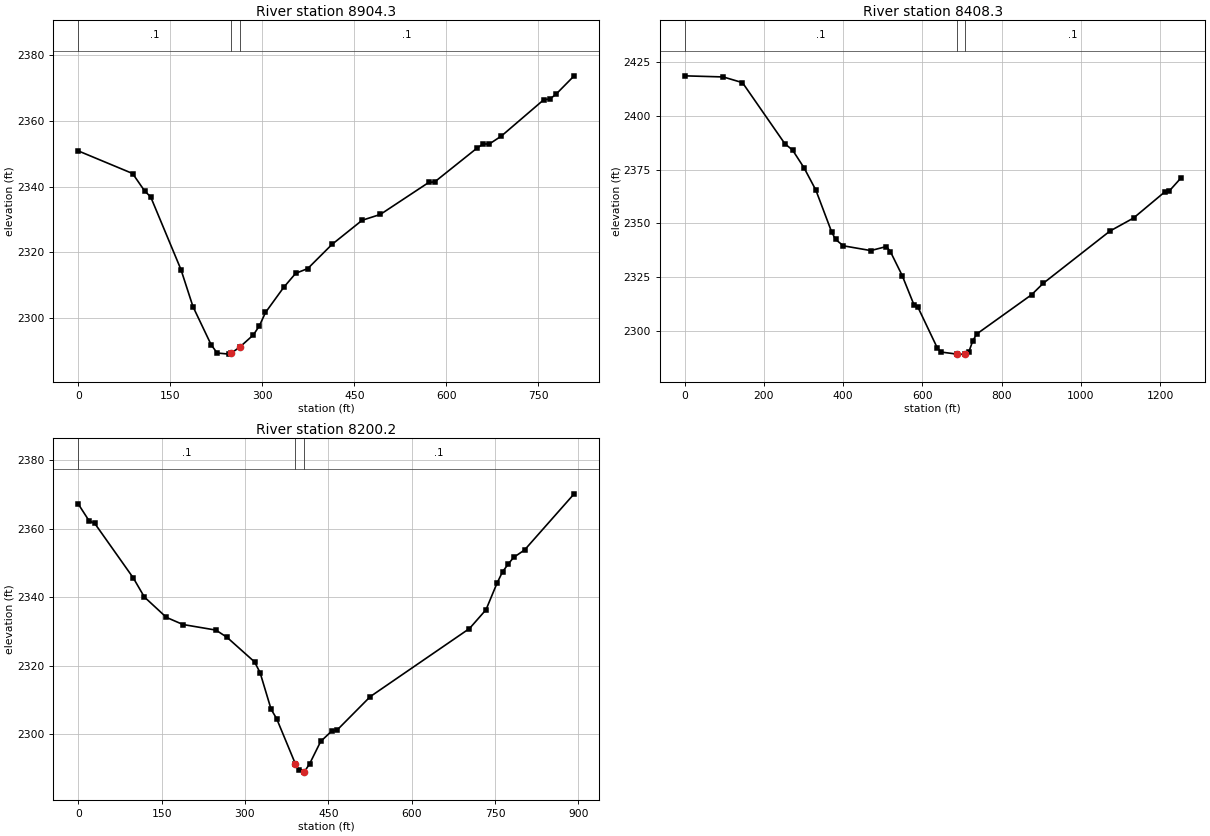
Type RM Length L Ch R = 1 ,8904.3  ,523.8,496.1,468.3
XS GIS Cut Line= 3
     1925800.658      256459.522     1925482.029      256821.696
     1925478.488      257147.483
#Sta/Elev= 30
       0 2350.86    88.6 2343.98   108.3 2338.66   118.1 2336.87   167.4 2314.79
     187 2303.51   216.6 2291.92   226.4  2289.4   246.1 2289.06   248.8 2289.28
   263.8 2291.28   285.5 2294.91   295.3 2297.69   305.2 2301.72   334.7 2309.32
   354.4 2313.63   374.1 2315.08   413.5 2322.41   462.7 2329.76   492.3 2331.53
   571.2 2341.26   581.1 2341.45   650.2 2351.75   660.1 2352.95     670 2352.96
   689.7 2355.38   758.8 2366.43   768.7 2366.63   778.6 2368.08   808.2 2373.68
#Mann= 3 , 0 , 0
       0      .1       0   248.8    .045       0   263.8      .1       0
Bank Sta=248.8,263.8
XS Rating Curve= 0 ,0
Exp/Cntr=0.3,0.1

Type RM Length L Ch R = 1 ,8408.3  ,208.9,208.1,207.4
XS GIS Cut Line= 4
     1924901.202      256001.531     1924999.415      256286.657
     1925374.024      256961.572     1925381.458      257139.735
#Sta/Elev= 30
       0 2418.65    97.3 2418.13   145.9 2415.47   252.9 2387.01   272.4 2384.05
   301.6  2375.7   331.2 2365.37   370.8 2345.99   380.7 2342.46   400.5 2339.46
   469.8 2337.24   509.4 2339.13   519.3 2336.73     549 2325.62   578.7    2312
   588.6 2310.91     638 2291.75   647.9 2289.95   687.5    2289   707.3    2289
   717.2 2290.05   727.1 2295.13     737 2298.36   875.6 2316.67   905.2 2322.02
  1073.5 2346.34  1132.9 2352.39  1212.2 2364.63  1222.1 2364.78  1251.8 2370.89
#Mann= 3 , 0 , 0
       0      .1       0   687.5    .045       0   707.3      .1       0
Bank Sta=687.5,707.3
XS Rating Curve= 0 ,0
Exp/Cntr=0.3,0.1

Type RM Length L Ch R = 1 ,8200.2  ,549.3,533,516.7
XS GIS Cut Line= 2
     1924816.096      256422.635     1925286.163      257180.995
#Sta/Elev= 30
       0 2367.21    19.8 2362.22    29.7 2361.53    99.1  2345.6     119 2340.03
   158.6 2334.09   188.4    2332   247.8 2330.37   267.7 2328.26   317.2 2321.09
   327.2 2317.95     347 2307.25   356.9 2304.54   390.7 2291.31   396.6 2289.55
   405.7 2288.95   406.5  2288.9   416.4 2291.36   436.2 2297.86     456 2300.88
   465.9 2301.21   525.4 2310.95   703.9 2330.83   733.6 2336.31   753.4 2344.06
   763.4  2347.4   773.3 2349.58   783.2 2351.58     803 2353.77   892.2 2370.16
#Mann= 3 , 0 , 0
       0      .1       0   390.7    .045       0   405.7      .1       0
Bank Sta=390.7,405.7
XS Rating Curve= 0 ,0
Exp/Cntr=0.3,0.1