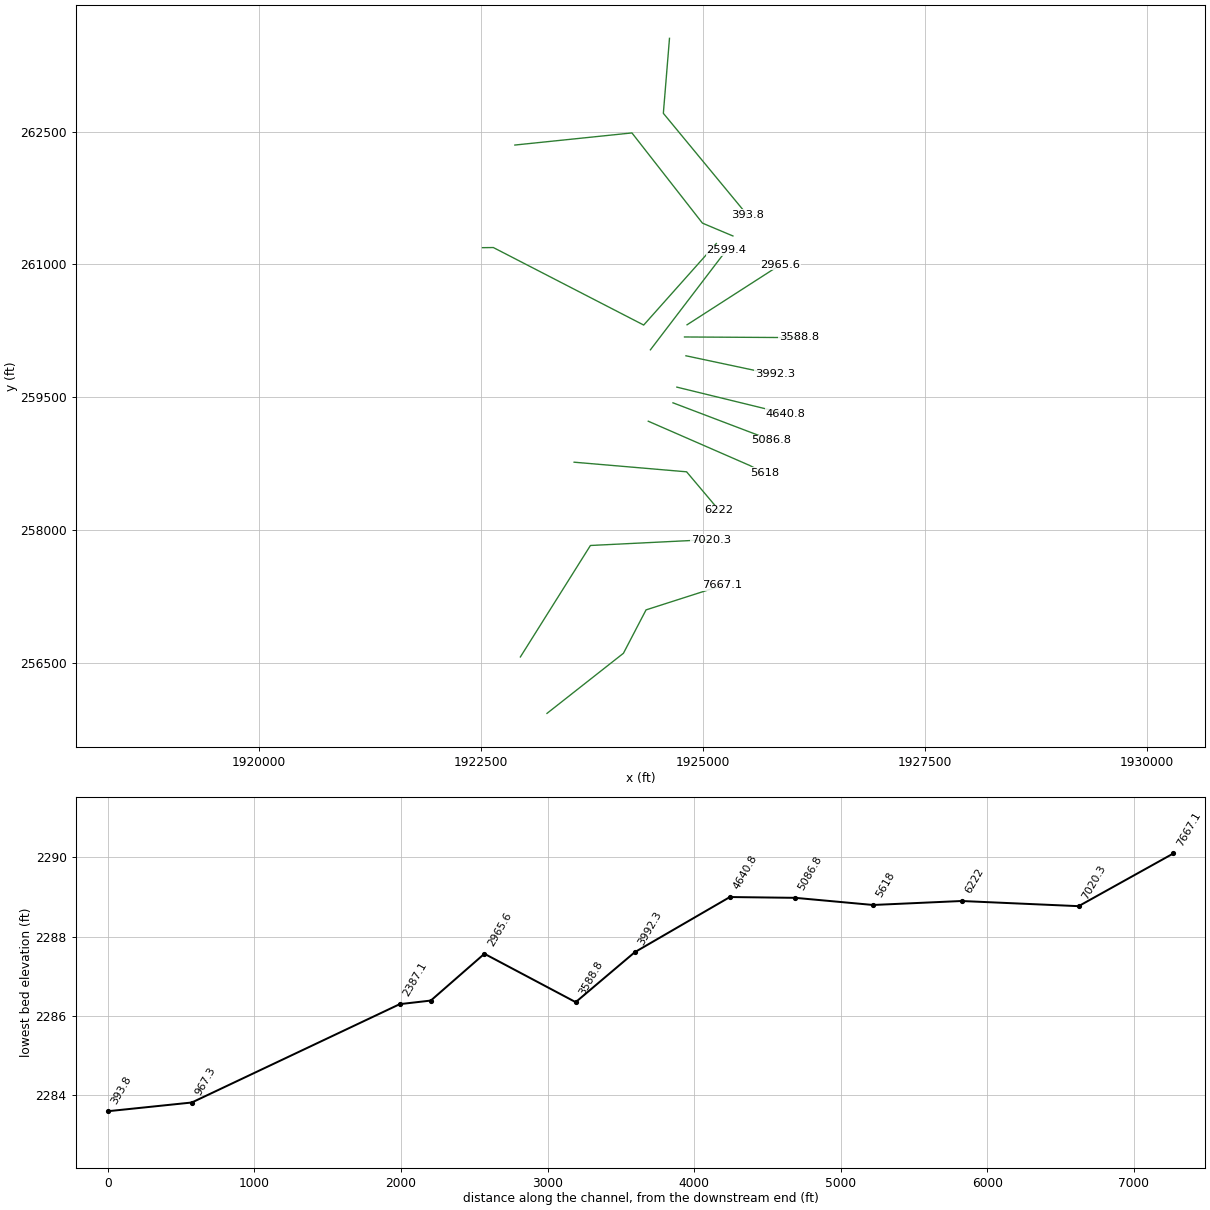
HEC-RAS study BvrCrk.prj: BvrCrk

--- BvrCrk.g01 (geometry) --- (continued)

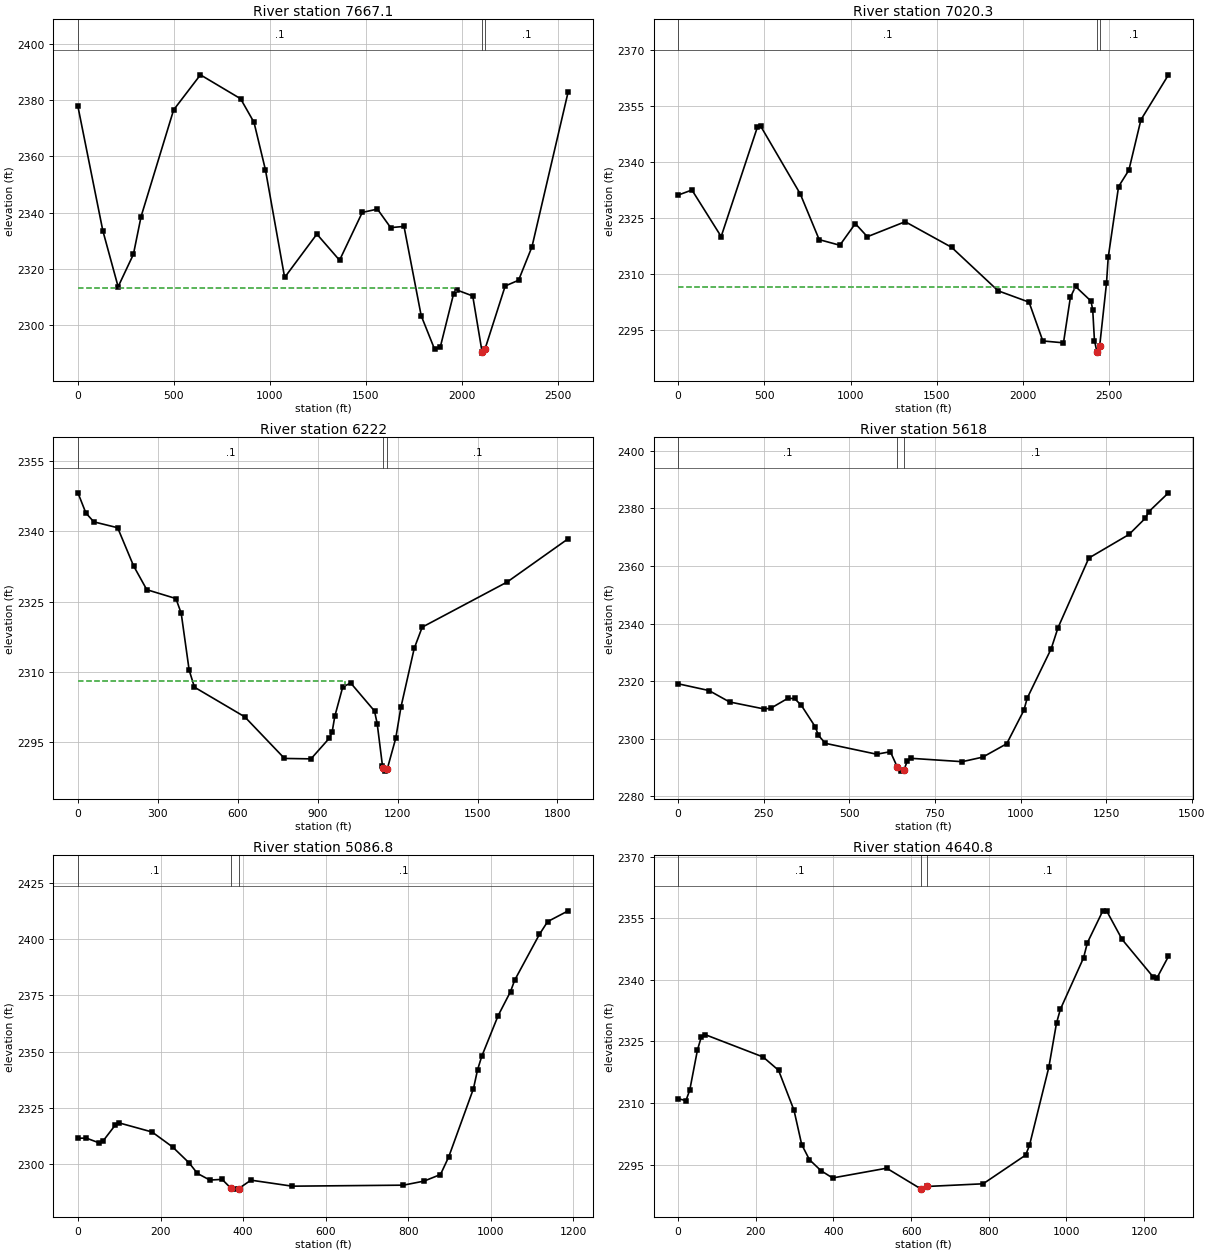
Type RM Length L Ch R = 1 ,7667.1  ,652.8,646.9,641
XS GIS Cut Line= 4
     1923243.075      255930.181     1924104.476      256608.941
     1924359.231      257098.782     1925221.006      257375.706
#Sta/Elev= 30
       0 2377.65   129.6 2333.59   209.4 2313.66   289.1  2325.2     329 2338.59
   498.5 2376.44   638.1 2388.89   847.4  2380.4   917.2 2372.02     977 2355.09
  1076.8 2316.95  1244.6 2332.35  1362.9 2323.07  1481.2 2340.05  1560.1 2341.22
  1629.1 2334.65  1698.6 2335.08  1788.1 2303.39  1857.7 2291.53  1887.5 2292.22
  1957.2 2311.24  1977.1 2312.43  2056.6 2310.39  2105.7 2290.37  2106.4  2290.1
  2120.7 2291.58  2225.7 2313.93  2295.4 2315.97    2365  2327.8    2554 2382.93
#Mann= 3 , 0 , 0
       0      .1       0  2105.7    .045       0  2120.7      .1       0
#XS Ineff= 2 , 0
         1969.47 2313.32
Permanent Ineff=
       F       F
Bank Sta=2105.7,2120.7
XS Rating Curve= 0 ,0
Exp/Cntr=0.3,0.1

Type RM Length L Ch R = 1 ,7020.3  ,801.2,798.2,795.1
XS GIS Cut Line= 3
     1922943.008      256567.165     1923732.363      257826.041
     1925087.779      257893.193
#Sta/Elev= 30
       0 2331.09    79.8 2332.45   249.3 2319.98   458.7 2349.19   478.7 2349.52
     708  2331.4   817.7 2319.16   937.4 2317.66  1027.2 2323.45    1097 2319.94
  1316.4 2323.96  1585.7  2317.1  1855.1 2305.46  2034.7 2302.42  2114.5 2292.03
  2234.3 2291.53  2274.2 2303.68  2304.1 2306.62  2393.9  2302.7  2403.9 2300.33
  2413.9 2292.12  2428.9 2289.04  2433.8 2288.77  2443.9 2290.57  2483.7 2307.48
  2493.7 2314.41  2553.6 2333.35  2613.5 2337.77  2683.3 2351.25    2843 2363.29
#Mann= 3 , 0 , 0
       0      .1       0  2428.9    .045       0  2443.9      .1       0
#XS Ineff= 2 , 0
         2294.66 2306.51
Permanent Ineff=
       F       F
Bank Sta=2428.9,2443.9
XS Rating Curve= 0 ,0
Exp/Cntr=0.3,0.1

Type RM Length L Ch R = 1 ,6222    ,600.6,603.9,590.5
XS GIS Cut Line= 3
     1923548.553      258766.681      1924816.29      258658.085
     1925182.211      258223.702
#Sta/Elev= 30
       0 2348.15    29.8 2343.86    59.6 2341.97   149.1 2340.72   208.8 2332.61
   258.4 2327.53   367.8 2325.64   387.7  2322.5   417.5  2310.4   437.4 2306.77
   626.2 2300.46   775.4  2291.6   874.8 2291.51   944.3 2295.95   954.3 2297.24
   964.2 2300.57     994 2306.81  1023.9 2307.66  1113.3  2301.7  1123.3 2299.03
  1143.2 2290.02  1146.5 2289.65  1153.1  2288.9  1161.5 2289.43  1192.9 2295.88
  1212.7 2302.57  1262.4 2315.04  1292.3 2319.55  1611.2 2329.16  1840.4 2338.38
#Mann= 3 , 0 , 0
       0      .1       0  1146.5    .045       0  1161.5      .1       0
#XS Ineff= 2 , 0
         1001.53  2308.1
Permanent Ineff=
       F       F
Bank Sta=1146.5,1161.5
XS Rating Curve= 0 ,0
Exp/Cntr=0.3,0.1

Type RM Length L Ch R = 1 ,5618    ,526.6,531,541.4
XS GIS Cut Line= 3
     1924384.268      259229.393     1925529.245      258728.908
     1925692.138      258646.281
#Sta/Elev= 30
       0 2319.11      90 2316.77     150 2312.81   249.9  2310.4   269.9 2310.58
   319.9 2314.04   339.9 2314.01   359.9 2311.61   399.9 2304.28   409.9  2301.2
   429.9 2298.45   579.8 2294.67   619.8 2295.54   639.8 2290.31   649.8  2288.8
   659.8 2289.27   669.8 2292.48   679.8 2293.25   829.7 2292.08   889.7 2293.66
   959.7  2298.3  1009.7 2309.87  1019.7 2314.16  1089.6 2331.26  1109.6 2338.58
  1199.6 2362.75  1316.9 2370.93  1364.9 2376.61  1374.6 2378.82  1432.2 2385.39
#Mann= 3 , 0 , 0
       0      .1       0   639.8    .045       0   659.8      .1       0
Bank Sta=639.8,659.8
XS Rating Curve= 0 ,0
Exp/Cntr=0.3,0.1

Type RM Length L Ch R = 1 ,5086.8  ,440.5,445.7,448.9
XS GIS Cut Line= 2
      1924662.84      259437.141     1925772.405      259014.562
#Sta/Elev= 30
       0 2311.56      20 2311.64    49.9  2309.6    59.9 2310.12    89.8 2317.25
    99.8 2318.37   179.6 2314.33   229.5 2307.65   269.4  2300.6   289.3 2295.96
   319.3 2293.01   349.2  2293.3     371 2289.29   379.1 2288.98   389.1 2289.19
     419 2292.96   518.8 2290.29   788.2 2290.74   838.1 2292.54     878 2295.46
     898 2303.32   957.8 2333.55   967.8 2341.97   977.8 2347.86  1017.7 2366.01
  1047.6 2376.64  1057.6 2381.69  1117.5    2402  1137.4 2407.69  1187.3 2412.48
#Mann= 3 , 0 , 0
       0      .1       0     371    .045       0   389.1      .1       0
Bank Sta=371,389.1
XS Rating Curve= 0 ,0
Exp/Cntr=0.3,0.1

Type RM Length L Ch R = 1 ,4640.8  ,649.9,648.5,649.1
XS GIS Cut Line= 2
     1924706.463      259614.362     1925932.937      259314.381
#Sta/Elev= 30
       0 2311.05    19.9 2310.56    29.8 2313.12    49.7 2322.93    59.6 2326.08
    69.6 2326.64   218.7  2321.2   258.5 2317.96   298.3 2308.21   318.1 2299.86
     338 2296.18   367.8 2293.49   397.7 2291.72   536.9  2294.1     626    2289
     641 2289.65   785.4  2290.3   894.8 2297.29   904.7 2299.67   954.4 2318.64
   974.3 2329.45   984.2 2332.81  1043.9 2345.34  1053.8 2349.03  1093.6 2356.81
  1103.6 2356.76  1143.3 2349.83  1222.9 2340.74  1232.8 2340.42  1262.6 2345.71
#Mann= 3 , 0 , 0
       0      .1       0     626    .045       0     641      .1       0
Bank Sta=626,641
XS Rating Curve= 0 ,0
Exp/Cntr=0.3,0.1

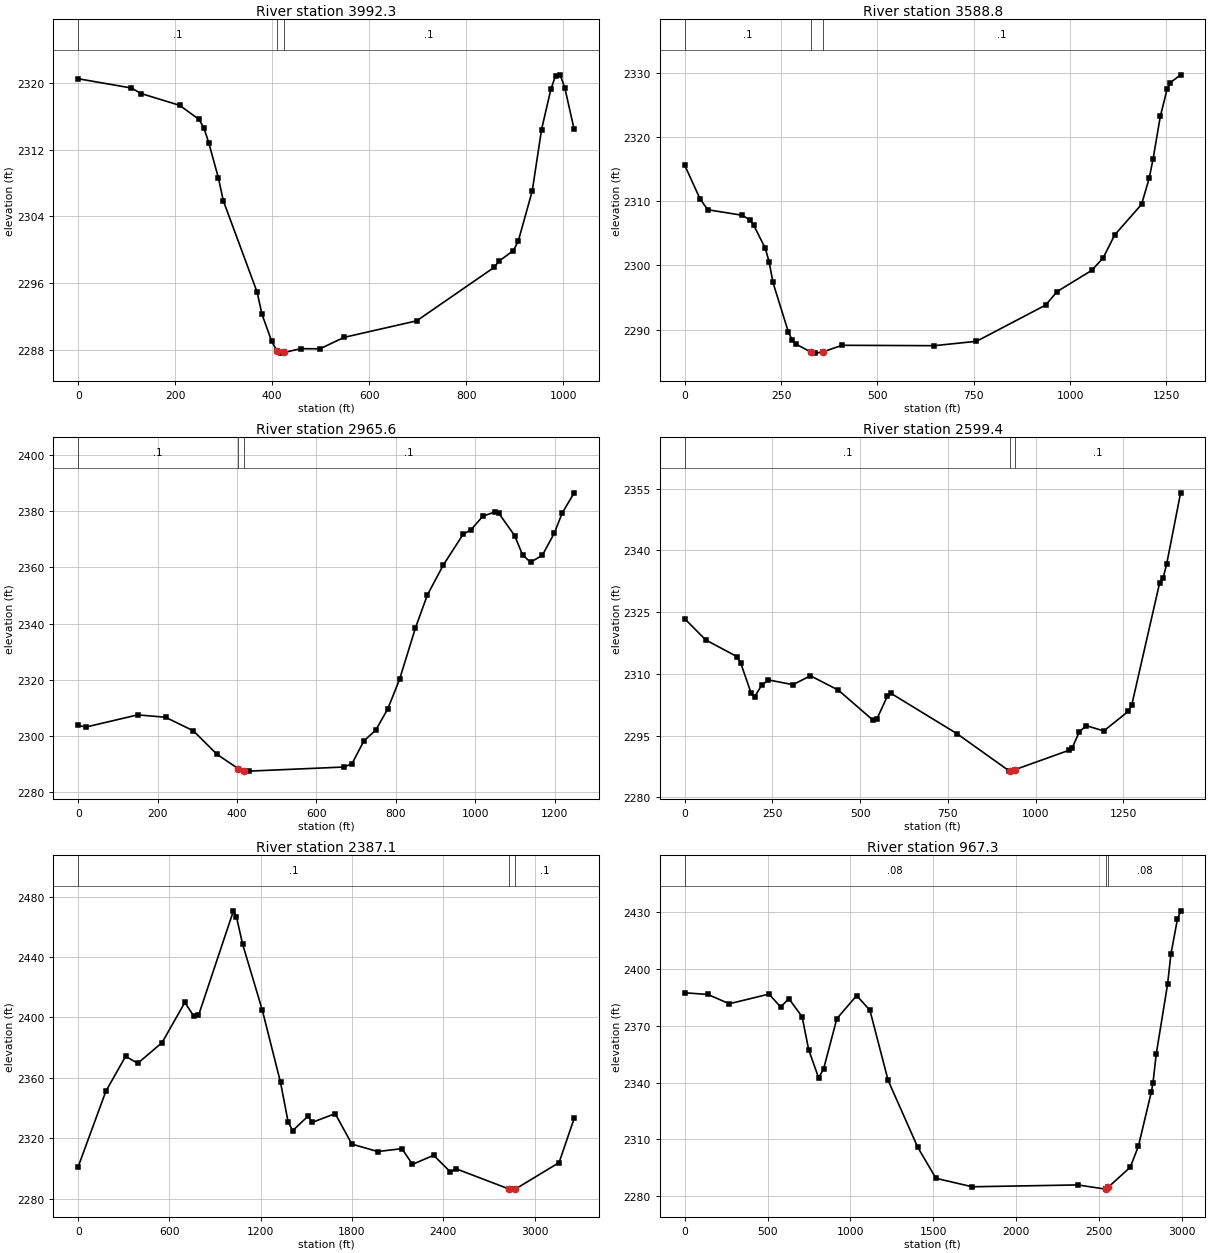
Type RM Length L Ch R = 1 ,3992.3  ,398.3,403.2,408.1
XS GIS Cut Line= 3
     1924809.208      259968.316      1925696.86      259779.454
     1925810.177      259758.207
#Sta/Elev= 30
       0 2320.48   109.7 2319.37   129.6 2318.71   209.4 2317.29   249.3  2315.6
   259.3 2314.58   269.3 2312.79   289.2 2308.58   299.2 2305.87     369 2294.91
     379 2292.26   398.9 2289.05   409.8 2287.89   418.9 2287.61   424.8 2287.69
   458.8 2288.14   498.6 2288.13   548.5  2289.5   698.1 2291.48   857.7 2297.88
   867.6 2298.62   897.6  2299.9   907.5 2301.02   936.3 2307.02   955.6  2314.4
   974.8 2319.22   984.4 2320.83     994 2320.95  1003.6 2319.37  1022.8 2314.41
#Mann= 3 , 0 , 0
       0      .1       0   409.8    .045       0   424.8      .1       0
Bank Sta=409.8,424.8
XS Rating Curve= 0 ,0
Exp/Cntr=0.3,0.1

Type RM Length L Ch R = 1 ,3588.8  ,600.3,622.6,639.7
XS GIS Cut Line= 3
     1924792.682      260180.785     1926017.925      260173.703
     1926079.305      260176.064
#Sta/Elev= 30
       0 2315.62    39.8 2310.38    59.8 2308.68   149.4 2307.82   169.4 2307.09
   179.3 2306.25   209.2 2302.66   219.2 2300.54   229.1 2297.35     269 2289.64
   278.9 2288.38   288.9 2287.76   328.7 2286.46   338.7 2286.35   358.6 2286.54
   408.4 2287.57   647.3 2287.51   757.1 2288.19   936.4 2293.83   966.3 2295.94
  1055.9 2299.23  1085.8 2301.18  1115.7 2304.76  1185.4 2309.52  1205.3 2313.61
  1215.3 2316.61    1234 2323.21  1251.6 2327.45  1260.4 2328.49  1286.7 2329.69
#Mann= 3 , 0 , 0
       0      .1       0   328.7    .045       0   358.6      .1       0
Bank Sta=328.7,358.6
XS Rating Curve= 0 ,0
Exp/Cntr=0.3,0.1

Type RM Length L Ch R = 1 ,2965.6  ,357.5,365.6,372.9
XS GIS Cut Line= 2
     1924821.425      260318.308     1925871.557      260995.253
#Sta/Elev= 30
       0 2303.81      20 2303.27   149.9 2307.58   219.9 2306.73   289.9 2301.93
   349.8 2293.53   403.2 2288.45   418.2 2287.72   429.8 2287.57   669.7 2289.03
   689.7  2290.2   719.7 2298.31   749.6 2302.17   779.6 2309.62   809.6 2320.24
   849.6 2338.52   879.6 2350.21   919.6 2360.83   969.5 2371.77   989.5 2373.44
  1019.5 2378.25  1049.5 2379.74  1059.5 2379.31  1099.5 2371.34  1119.5 2364.49
  1139.5 2361.86  1169.4 2364.37  1199.4 2372.21  1219.4  2379.4  1249.4 2386.56
#Mann= 3 , 0 , 0
       0      .1       0   403.2    .045       0   418.2      .1       0
Bank Sta=403.2,418.2
XS Rating Curve= 0 ,0
Exp/Cntr=0.3,0.1

Type RM Length L Ch R = 1 ,2599.4  ,212.7,211.9,211.1
XS GIS Cut Line= 2
     1924408.401      260035.598     1925264.575      261160.376
#Sta/Elev= 30
       0 2323.39    59.7 2318.26   149.3 2314.18   159.3 2312.74   189.1 2305.38
   199.1 2304.38     219  2307.2   238.9 2308.53   308.6 2307.38   358.4 2309.54
     438 2306.05   537.6  2298.7   547.5    2299   577.4 2304.51   587.3 2305.31
   776.5 2295.46   925.8 2286.39   927.4 2286.42   942.4 2286.78    1095 2291.44
    1105 2292.11  1124.9 2295.94  1144.8 2297.43  1194.6 2296.15  1264.2 2300.89
  1274.2  2302.4  1353.8  2332.1  1363.8 2333.32  1373.8 2336.67  1413.6 2353.96
#Mann= 3 , 0 , 0
       0      .1       0   927.4    .045       0   942.4      .1       0
Bank Sta=927.4,942.4
XS Rating Curve= 0 ,0
Exp/Cntr=0.3,0.1

Type RM Length L Ch R = 1 ,2387.1  ,1456.8,1418.4,1378.1
XS GIS Cut Line= 4
     1922516.597      261189.252     1922638.429      261190.709
     1924332.793      260315.373     1925151.258      261235.921
#Sta/Elev= 30
       0 2301.19   181.8  2351.1   311.6 2374.26   391.4 2369.62   551.2 2383.32
     701  2409.9   760.9 2400.71   790.8  2401.3  1020.5  2470.6  1040.4 2466.68
  1080.4  2448.7  1210.2 2404.91    1330 2357.03  1379.9 2330.92  1409.9 2324.98
  1509.7 2334.54  1539.7 2330.56  1689.5 2336.28  1799.3 2316.11    1969  2311.2
  2128.3  2313.1  2197.8  2302.7  2336.9 2308.72  2446.2 2297.78  2485.9 2299.72
  2833.6 2286.33  2843.5  2286.3  2873.3  2286.3  3161.4 2303.85  3260.7 2333.09
#Mann= 3 , 0 , 0
       0      .1       0  2833.6    .045       0  2873.3      .1       0
Bank Sta=2833.6,2873.3
XS Rating Curve= 0 ,0
Exp/Cntr=0.3,0.1

Type RM Length L Ch R = 1 ,967.3   ,573,573.3,573.9
XS GIS Cut Line= 4
     1922880.716      262348.109     1924200.255      262484.955
     1924994.922      261466.228     1925338.022      261321.434
#Sta/Elev= 30
       0 2387.33   139.6 2386.43   269.3 2381.54   508.7 2386.64   578.5 2379.84
   628.4 2384.21   708.2 2374.68   748.1 2357.22   807.9 2342.46   837.9 2347.23
   917.7 2373.67  1037.4 2385.87  1117.2 2378.06  1226.9 2341.15  1406.1 2305.79
  1515.4 2289.52  1734.1 2285.06  2370.2 2286.03  2538.4 2283.83  2539.1 2283.82
  2553.4 2284.75  2687.2 2295.37  2736.2 2306.39  2814.6 2335.15  2824.4 2339.93
    2844 2355.04  2912.6 2391.98  2932.2 2407.56  2971.4 2425.99    2991 2430.53
#Mann= 3 , 0 , 0
       0     .08       0  2538.4    .045       0  2553.4     .08       0
Bank Sta=2538.4,2553.4
XS Rating Curve= 0 ,0
Exp/Cntr=0.3,0.1

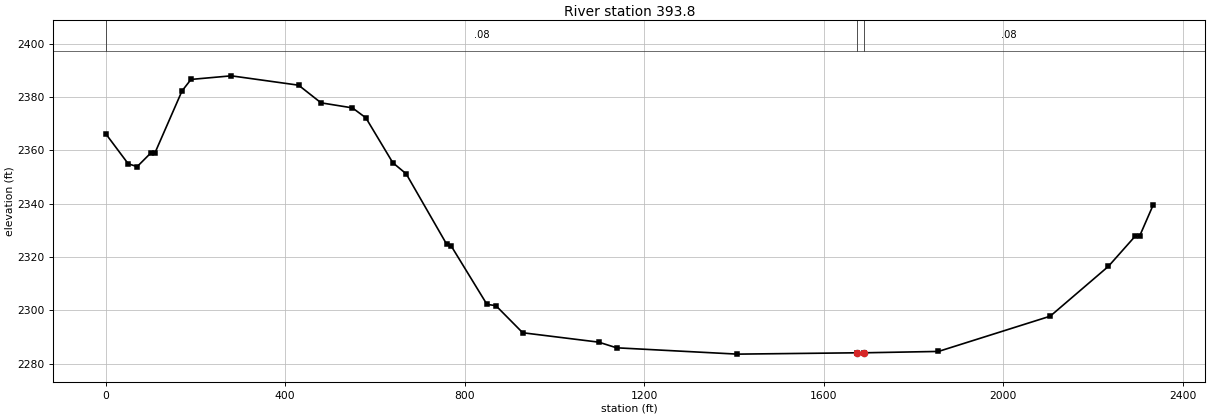
Type RM Length L Ch R = 1 ,393.8   ,398.9,393.6,386.7
XS GIS Cut Line= 3
     1924623.494      263553.154     1924554.244      262706.422
     1925498.555      261560.659
#Sta/Elev= 30
       0 2366.16      50 2354.92      70 2353.87     100 2358.92   109.9 2359.12
   169.9 2382.22   189.9 2386.54   279.8 2387.89   429.8 2384.38   479.8 2377.77
   549.7 2375.88   579.7 2372.15   639.7 2355.34   669.6 2351.16   759.6 2324.84
   769.6 2324.22   849.6 2302.24   869.5 2301.77   929.3 2291.61  1098.7 2288.09
  1138.5 2285.97  1407.6  2283.6  1675.2  2284.1  1690.2  2284.1    1856 2284.61
  2105.1 2297.82  2234.7 2316.48  2294.4 2327.79  2304.4 2327.84  2334.3 2339.39
#Mann= 3 , 0 , 0
       0     .08       0  1675.2    .045       0  1690.2     .08       0
Bank Sta=1675.2,1690.2
XS Rating Curve= 0 ,0
Exp/Cntr=0.3,0.1

Chan Stop Cuts=-1
Use User Specified Reach Order=0
Composite Channel Slope=5